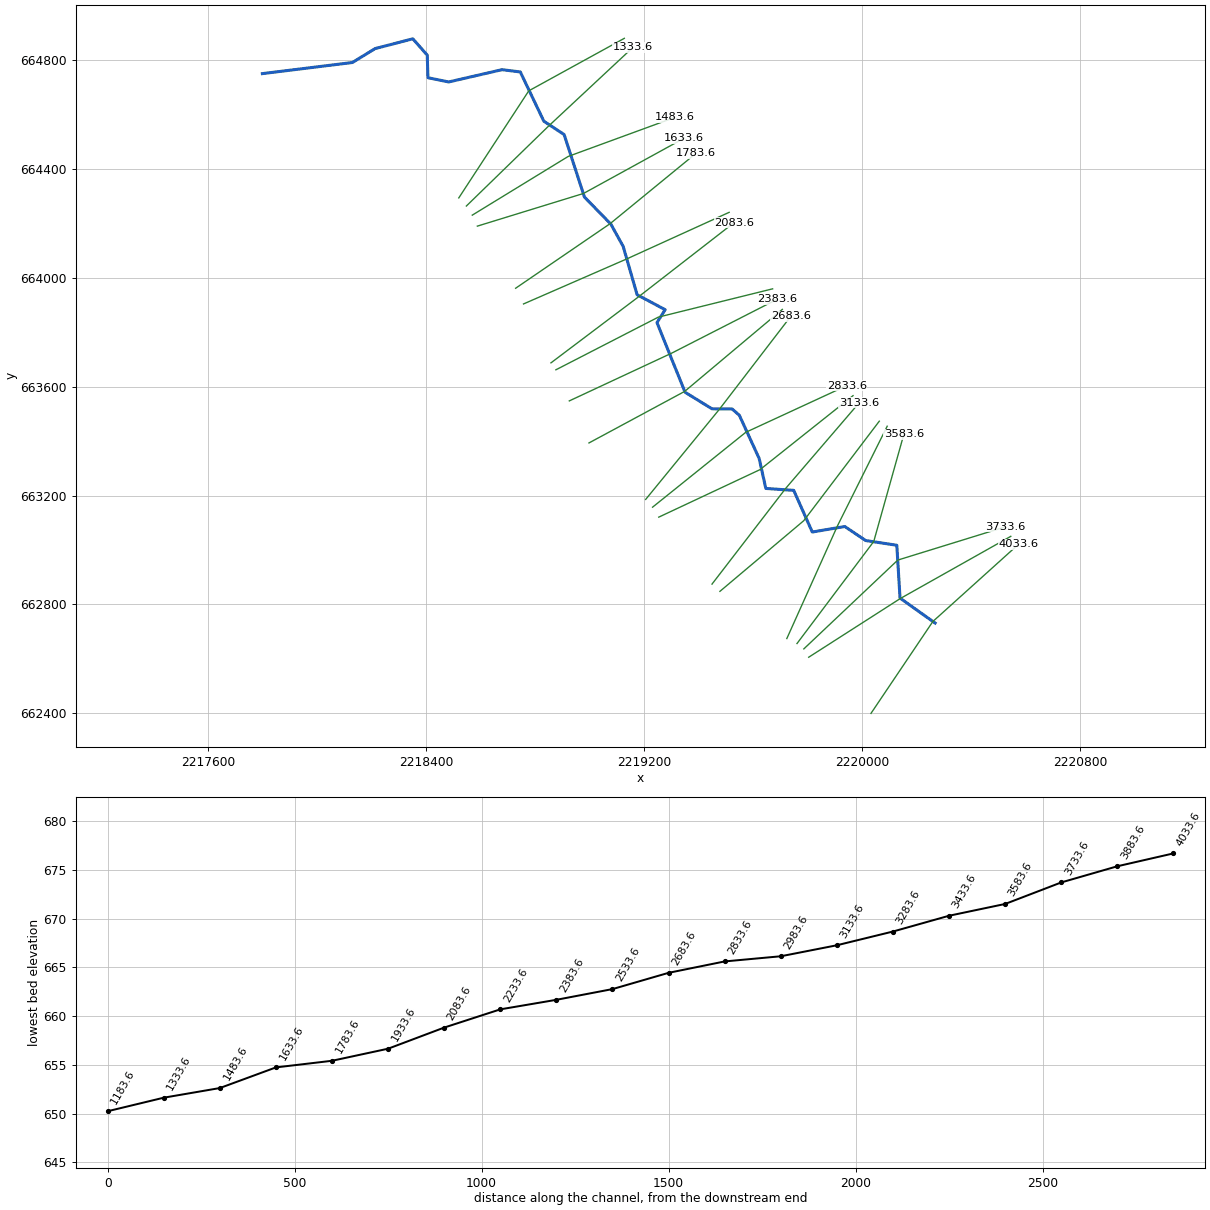
--- JENKSFKT1.prj (project) ---

Proj Title=JENKSFKT1
Current Plan=p01
Geom File=g01
Flow File=f01
Plan File=p01
DSS Export Rating Curves=0
DSS Export Rating Curve Sorted=0
DSS Export Volume Flow Curves=0
DXF OffsetX=0
DXF OffsetY=0
DXF ScaleX=0
DXF ScaleY=0

--- JENKSFKT1.p01 (plan) ---

Plan Title=Floodplain
Program Version=4.00
Geom File=g01
Flow File=f01
K Sum by GR=0
Std Step Tol=0.01
Critical Tol=0.01
Num of Std Step Trials=20
Max Error Tol=0.3
Flow Tol Ratio=0.001
Split Flow NTrial=30
Split Flow Tol=0.02
Split Flow Ratio=0.02
Log Output Level=0
Friction Slope Method=1
Unsteady Friction Slope Method=2
Unsteady Bridges Friction Slope Method=1
Global Log Level=0
CheckData=False
Run HTab=0
Run UNet=0
Run PostProcess=0
UNET Theta=0
UNET Theta Warmup=0
UNET ZTol=0
UNET ZSATol=0
UNET MxIter=0
UNET MaxInSteps=0
UNET DtIC=0
UNET DtMin=0
UNET MaxCRTS=0
UNET WFStab=0
UNET SFStab=0
UNET WFX=0
UNET SFX=0
UNET DSS MLevel=0
UNET DZMax Abort=0
UNET Convert EG Bridges=0
UNET Use Existing IB Tables=0
UNET Froude Limit=0
UNET Froude Power=0
Write IC File=0
Echo Input=False
Echo Output=False
Write Detailed=0

--- JENKSFKT1.f01 (steady flow) ---

Flow Title=Flows
Program Version=4.00
Number of Profiles= 1
Profile Names=01pct
River Rch & RM=JENKSFKT1,Main      ,4033.6
295.4803
River Rch & RM=JENKSFKT1,Main      ,3883.6
296.9693
River Rch & RM=JENKSFKT1,Main      ,3583.6
304.2420
River Rch & RM=JENKSFKT1,Main      ,3283.6
305.9943
River Rch & RM=JENKSFKT1,Main      ,2983.6
310.5236
River Rch & RM=JENKSFKT1,Main      ,2683.6
319.2168
River Rch & RM=JENKSFKT1,Main      ,2383.6
321.2792
River Rch & RM=JENKSFKT1,Main      ,2083.6
323.9015
River Rch & RM=JENKSFKT1,Main      ,1783.6
326.1963
River Rch & RM=JENKSFKT1,Main      ,1483.6
333.7348
River Rch & RM=JENKSFKT1,Main      ,1183.6
339.5333
Boundary for River Rch & Prof#=JENKSFKT1,Main      ,1
Up Type=0
Dn Type=3
Dn Slope=0.008311

--- JENKSFKT1.g01 (geometry) ---

Geom Title=Geometry
Program Version=4.00

River Reach=JENKSFKT1     ,Main
Reach XY= 30
     2220267.207      662731.642     2220138.576      662823.444
     2220126.729      663017.635     2220012.493      663035.005
     2219935.915      663086.600     2219816.613      663066.311
     2219748.506      663219.466     2219646.146      663226.506
     2219621.679      663336.908     2219548.964      663495.557
     2219522.523      663518.707     2219448.492      663519.366
     2219349.966      663580.175     2219246.775      663836.206
     2219276.765      663883.709     2219173.947      663938.710
     2219122.752      664116.389     2219077.624      664198.289
     2218980.614      664297.903     2218906.126      664527.635
     2218831.666      664576.713     2218745.359      664757.797
     2218678.339      664766.153     2218482.632      664720.968
     2218406.484      664736.621     2218403.937      664819.551
     2218351.054      664879.646     2218212.693      664843.675
     2218129.363      664792.480     2217798.958      664751.616

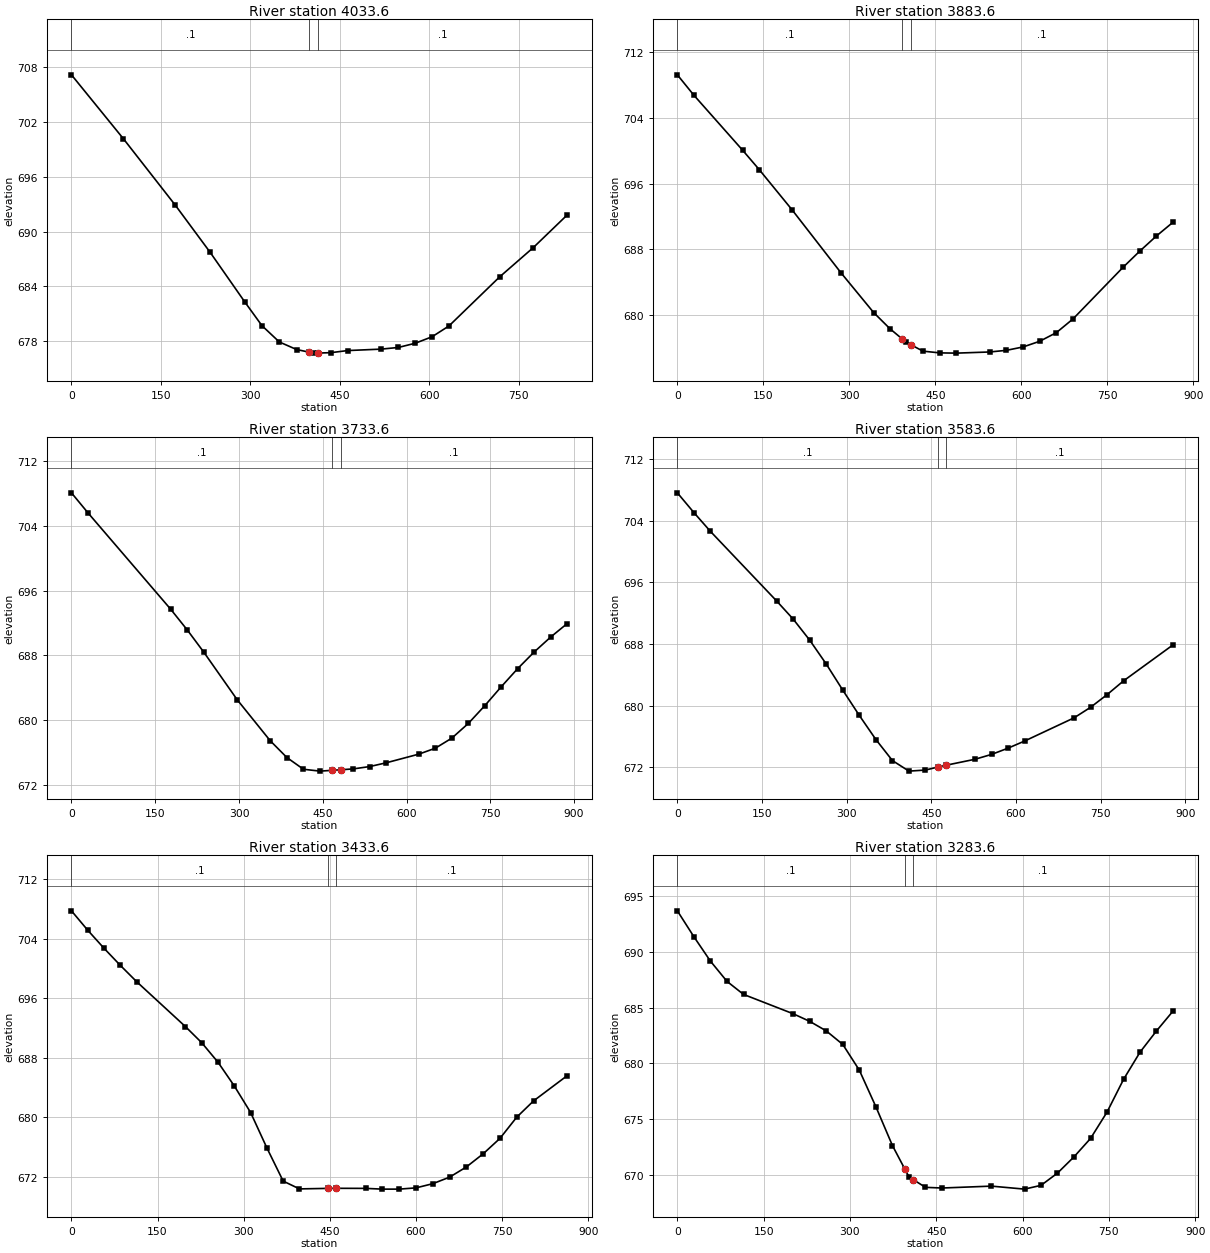
Type RM Length L Ch R = 1 ,4033.6,158.3,150,144
XS GIS Cut Line= 3
     2220032.004      662399.562     2220258.907      662737.220
     2220574.039      663021.964
#Sta/Elev= 21
       0  707.12    87.2  700.13   174.4  692.86   232.5  687.74   290.6  682.32
   319.6  679.71   348.7  677.93   377.8  677.10   399.3  676.81   406.8  676.71
   414.3  676.72   435.1  676.76   463.4  676.99   520.1  677.15   548.4  677.33
   576.7  677.79   605.0  678.50   633.3  679.68   718.3  685.04   774.9  688.25
   831.5  691.80
#Mann= 3 , 0 , 0
       0     0.1       0   399.3   0.045       0   414.3     0.1       0
Bank Sta=399.3,414.3
Exp/Cntr=0.3,0.1

Type RM Length L Ch R = 1 ,3883.6,135.9,150,148.1
XS GIS Cut Line= 3
     2219803.479      662605.968     2220139.670      662821.843
     2220544.854      663050.389
#Sta/Elev= 24
       0  709.22    28.5  706.77   114.2  700.03   142.7  697.71   199.8  692.84
   285.4  685.16   342.5  680.32   371.0  678.35     392  677.13   399.5  676.70
     407  676.42   428.6  675.63   457.7  675.42   486.8  675.39   544.9  675.53
   574.0  675.73   603.1  676.14   632.1  676.83   661.2  677.88   690.3  679.55
   777.5  685.82   806.6  687.78   835.6  689.62   864.7  691.30
#Mann= 3 , 0 , 0
       0     0.1       0     392   0.045       0     407     0.1       0
Bank Sta=392,407
Exp/Cntr=0.3,0.1

Type RM Length L Ch R = 1 ,3733.6,155.3,150,168.4
XS GIS Cut Line= 3
     2219785.619      662636.644     2220130.246      662963.136
     2220524.572      663085.191
#Sta/Elev= 25
       0  708.05    29.7  705.57   178.0  693.67   207.7  691.11   237.4  688.36
   296.7  682.54   356.0  677.47   385.7  675.41   415.4  673.96   445.1  673.73
   467.2  673.83   482.2  673.90   504.2  674.00   533.7  674.29   563.2  674.75
   622.2  675.83   651.6  676.56   681.1  677.80   710.6  679.61   740.1  681.80
   769.6  684.14   799.1  686.38   828.5  688.42   858.0  690.26   887.5  691.92
#Mann= 3 , 0 , 0
       0     0.1       0   467.2   0.045       0   482.2     0.1       0
Bank Sta=467.2,482.2
Exp/Cntr=0.3,0.1

Type RM Length L Ch R = 1 ,3583.6,144.9,150,145.3
XS GIS Cut Line= 3
     2219760.548      662656.371     2220042.130      663031.488
     2220152.615      663425.580
#Sta/Elev= 24
       0  707.63    29.3  705.07    58.6  702.63   175.9  693.60   205.2  691.25
   234.5  688.52   263.8  685.42   293.2  682.02   322.5  678.74   351.8  675.62
   381.1  672.89   410.4  671.52   439.7  671.66   461.5  672.05   476.5  672.29
   527.5  673.06   556.8  673.69   586.0  674.50   615.2  675.42   702.9  678.43
   732.2  679.80   761.4  681.44   790.6  683.23   878.3  687.90
#Mann= 3 , 0 , 0
       0     0.1       0   461.5   0.045       0   476.5     0.1       0
Bank Sta=461.5,476.5
Exp/Cntr=0.3,0.1

Type RM Length L Ch R = 1 ,3433.6,157.8,150,146
XS GIS Cut Line= 3
     2219723.256      662674.660     2219909.007      663088.893
     2220091.497      663455.365
#Sta/Elev= 27
       0  707.73    28.4  705.12    56.8  702.69    85.1  700.40   113.5  698.21
   198.6  692.16   227.0  689.99   255.4  687.36   283.7  684.18   312.1  680.61
   340.5  675.84   368.8  671.39   397.2  670.34   446.5  670.41   461.5  670.42
   512.5  670.41   541.7  670.31   570.9  670.31   600.2  670.48   629.4  671.04
   658.7  671.92   687.9  673.29   717.2  675.06   746.4  677.13   775.6  679.98
   804.9  682.17   863.4  685.56
#Mann= 3 , 0 , 0
       0     0.1       0   446.5   0.045       0   461.5     0.1       0
Bank Sta=446.5,461.5
Exp/Cntr=0.3,0.1

Type RM Length L Ch R = 1 ,3283.6,155.1,150,143.1
XS GIS Cut Line= 3
     2219477.796      662848.213     2219785.362      663107.969
     2220062.490      663473.815
#Sta/Elev= 28
       0  693.70    28.8  691.37    57.5  689.18    86.3  687.36   115.0  686.19
   201.3  684.45   230.0  683.77   258.8  682.91   287.6  681.69   316.3  679.38
   345.1  676.09   373.8  672.61   395.1  670.52   402.6  669.79   410.1  669.54
   431.3  668.85   460.0  668.79   546.0  668.96   603.4  668.69   632.1  669.03
   660.7  670.13   689.4  671.59   718.1  673.24   746.8  675.61   775.5  678.55
   804.2  681.00   832.8  682.91   861.5  684.69
#Mann= 3 , 0 , 0
       0     0.1       0   395.1   0.045       0   410.1     0.1       0
Bank Sta=395.1,410.1
Exp/Cntr=0.3,0.1

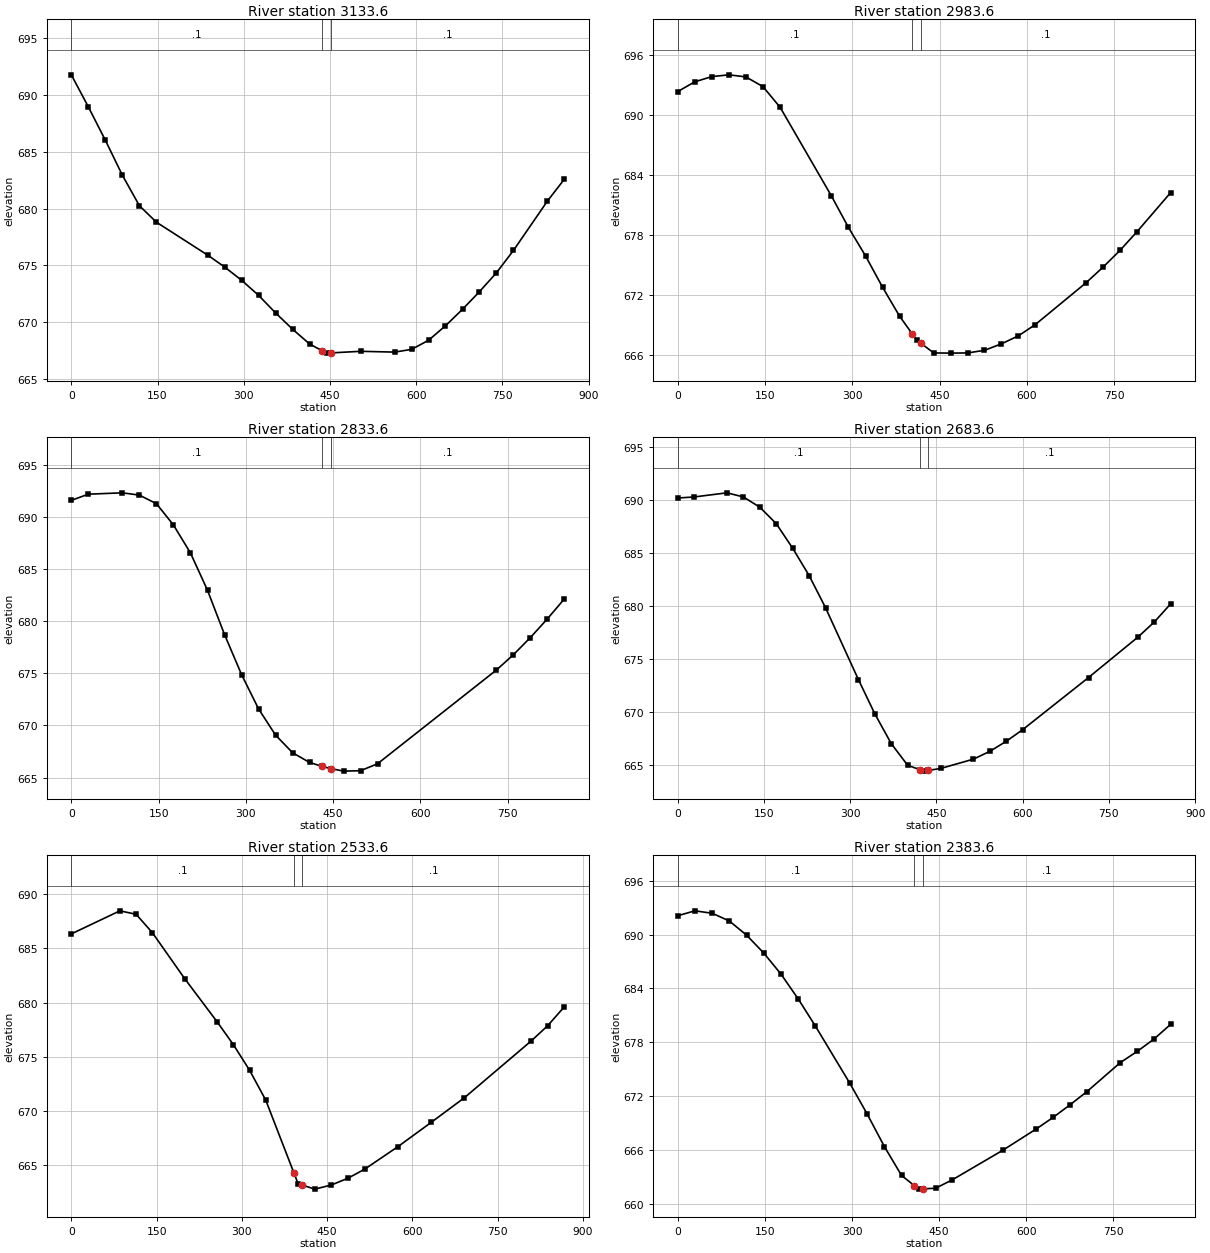
Type RM Length L Ch R = 1 ,3133.6,150.1,150,150.3
XS GIS Cut Line= 3
     2219448.733      662874.859     2219719.414      663227.198
     2219988.420      663541.214
#Sta/Elev= 27
       0  691.79    29.6  688.97    59.2  686.03    88.9  682.94   118.5  680.26
   148.1  678.81   237.0  675.92   266.6  674.87   296.2  673.70   325.8  672.37
   355.4  670.82   385.1  669.38   414.7  668.08   436.8  667.48   444.3  667.28
   451.8  667.30   503.4  667.44   562.4  667.37   592.0  667.61   621.5  668.41
   651.0  669.69   680.6  671.14   710.1  672.69   739.7  674.36   769.2  676.32
   828.3  680.67   857.8  682.60
#Mann= 3 , 0 , 0
       0     0.1       0   436.8   0.045       0   451.8     0.1       0
Bank Sta=436.8,451.8
Exp/Cntr=0.3,0.1

Type RM Length L Ch R = 1 ,2983.6,144.6,150,141.3
XS GIS Cut Line= 3
     2219253.428      663121.037     2219624.969      663295.760
     2219966.108      663567.696
#Sta/Elev= 27
       0  692.35    29.3  693.33    58.6  693.85    88.0  694.03   117.3  693.82
   146.6  692.84   176.0  690.77   263.9  681.91   293.3  678.74   322.6  675.89
   351.9  672.75   381.2  669.84   403.1  668.06   410.6  667.45   418.1  667.12
   439.7  666.17   468.7  666.15   497.8  666.17   526.9  666.43   556.0  667.08
   585.1  667.88   614.2  669.01   701.4  673.20   730.5  674.76   759.6  676.44
   788.7  678.30   846.8  682.24
#Mann= 3 , 0 , 0
       0     0.1       0   403.1   0.045       0   418.1     0.1       0
Bank Sta=403.1,418.1
Exp/Cntr=0.3,0.1

Type RM Length L Ch R = 1 ,2833.6,150.4,150,156.7
XS GIS Cut Line= 3
     2219230.657      663157.682     2219572.510      663432.892
     2219943.226      663604.521
#Sta/Elev= 24
       0  691.59    29.3  692.18    87.8  692.31   117.0  692.09   146.3  691.27
   175.6  689.22   204.8  686.54   234.1  682.96   263.3  678.72   292.6  674.88
   321.8  671.59   351.1  669.07   380.4  667.38   409.6  666.45   431.4  666.07
   446.4  665.86   468.0  665.62   497.2  665.66   526.4  666.33   730.7  675.32
   759.8  676.78   789.0  678.43   818.2  680.22   847.4  682.14
#Mann= 3 , 0 , 0
       0     0.1       0   431.4   0.045       0   446.4     0.1       0
Bank Sta=431.4,446.4
Exp/Cntr=0.3,0.1

Type RM Length L Ch R = 1 ,2683.6,153.3,150,148.9
XS GIS Cut Line= 3
     2219205.374      663186.185     2219476.328      663518.285
     2219737.195      663858.696
#Sta/Elev= 25
       0  690.22    28.6  690.32    85.7  690.71   114.3  690.32   142.9  689.35
   171.4  687.80   200.0  685.48   228.6  682.90   257.2  679.86   314.3  673.09
   342.9  669.85   371.5  667.04   400.0  665.00   421.1  664.59   428.6  664.45
   436.1  664.52   457.2  664.70   514.4  665.58   543.0  666.32   571.6  667.27
   600.2  668.37   714.5  673.28   800.3  677.09   828.9  678.52   857.5  680.24
#Mann= 3 , 0 , 0
       0     0.1       0   421.1   0.045       0   436.1     0.1       0
Bank Sta=421.1,436.1
Exp/Cntr=0.3,0.1

Type RM Length L Ch R = 1 ,2533.6,150.8,150,144.8
XS GIS Cut Line= 3
     2218997.270      663393.800     2219348.394      663583.300
     2219706.752      663884.869
#Sta/Elev= 22
       0  686.33    85.5  688.46   114.0  688.14   142.5  686.45   199.5  682.20
   256.5  678.22   285.0  676.12   313.5  673.76   342.0  671.00   391.5  664.29
   399.0  663.28   406.5  663.15   428.3  662.78   457.5  663.16   486.8  663.79
   516.1  664.62   574.6  666.70   633.2  668.94   691.7  671.22   808.8  676.44
   838.1  677.86   867.4  679.61
#Mann= 3 , 0 , 0
       0     0.1       0   391.5   0.045       0   406.5     0.1       0
Bank Sta=391.5,406.5
Exp/Cntr=0.3,0.1

Type RM Length L Ch R = 1 ,2383.6,144.4,150,162.6
XS GIS Cut Line= 3
     2218925.162      663548.403     2219301.085      663724.109
     2219687.092      663921.688
#Sta/Elev= 27
       0  692.09    29.6  692.64    59.3  692.37    88.9  691.51   118.6  689.93
   148.2  687.94   177.8  685.60   207.5  682.83   237.1  679.81   296.4  673.44
   326.0  670.05   355.7  666.42   385.3  663.20   407.5  662.06   415.0  661.68
   422.5  661.71   443.9  661.78   472.8  662.72   559.5  666.00   617.3  668.38
   646.2  669.66   675.1  671.05   704.0  672.51   761.9  675.76   790.8  677.00
   819.7  678.37   848.6  680.02
#Mann= 3 , 0 , 0
       0     0.1       0   407.5   0.045       0   422.5     0.1       0
Bank Sta=407.5,422.5
Exp/Cntr=0.3,0.1

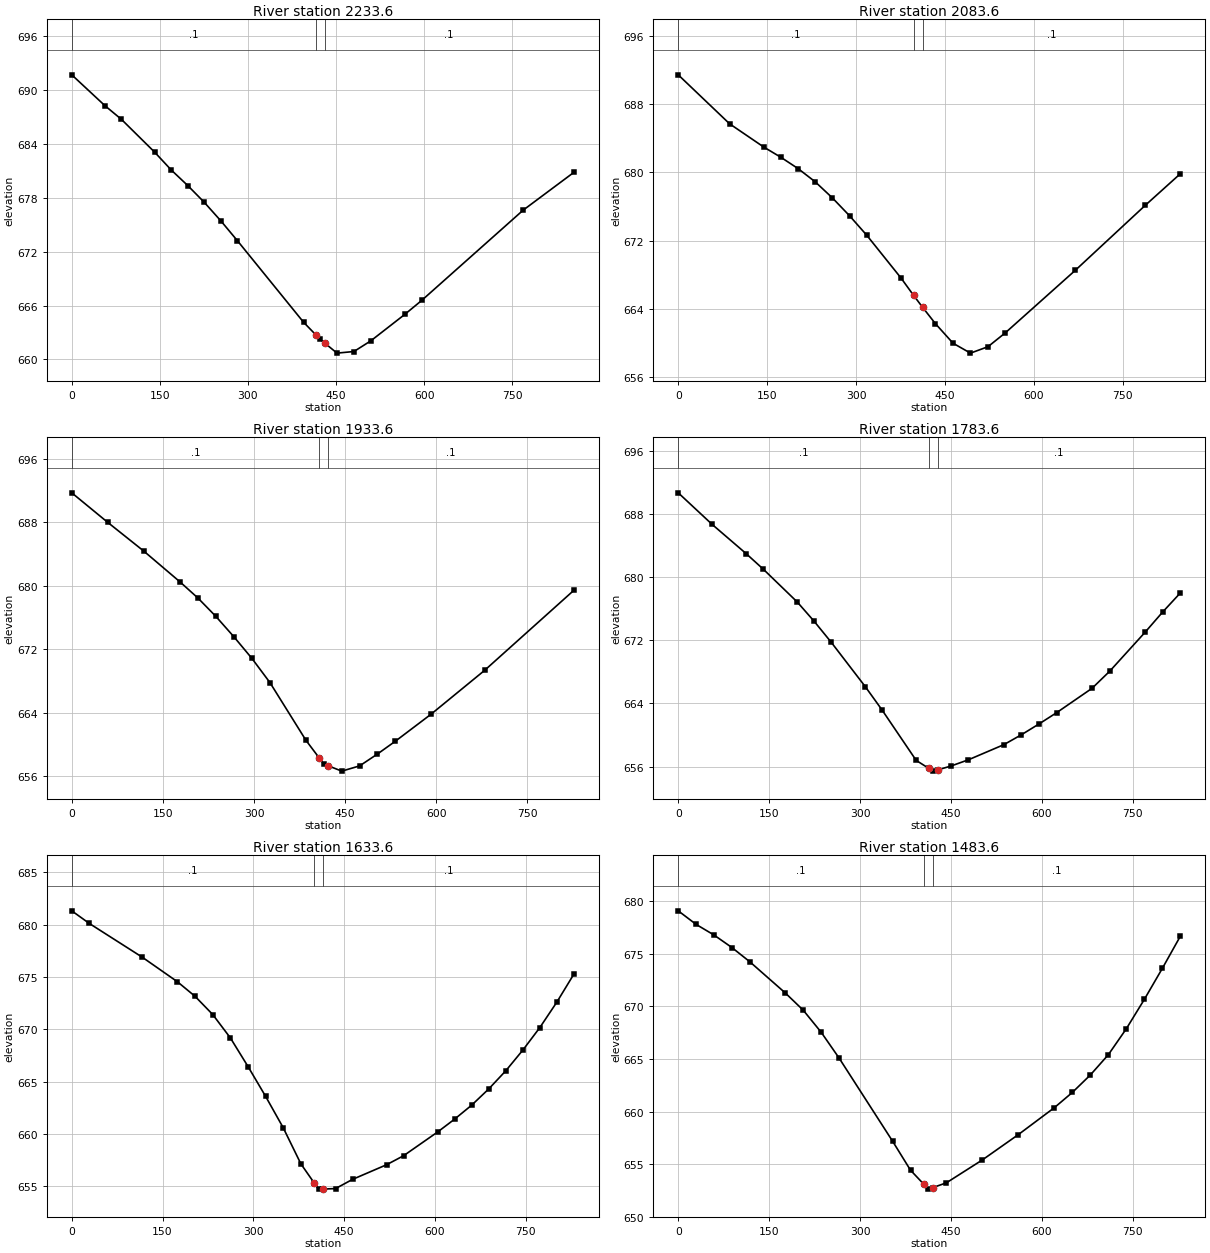
Type RM Length L Ch R = 1 ,2233.6,130.7,150,142.4
XS GIS Cut Line= 3
     2218875.857      663662.653     2219251.805      663856.380
     2219671.143      663960.423
#Sta/Elev= 20
       0  691.68    56.4  688.25    84.6  686.72   141.0  683.08   169.2  681.10
   197.4  679.36   225.6  677.49   253.8  675.43   282.0  673.22   394.7  664.14
   415.4  662.75   422.9  662.24   430.4  661.84   451.7  660.70   480.5  660.88
   509.3  662.07   566.9  665.00   595.8  666.56   768.6  676.61   855.0  680.82
#Mann= 3 , 0 , 0
       0     0.1       0   415.4   0.045       0   430.4     0.1       0
Bank Sta=415.4,430.4
Exp/Cntr=0.3,0.1

Type RM Length L Ch R = 1 ,2083.6,155,150,144.1
XS GIS Cut Line= 3
     2218857.783      663688.167     2219180.523      663932.109
     2219529.682      664203.780
#Sta/Elev= 20
       0  691.43    86.7  685.69   144.5  682.96   173.4  681.76   202.3  680.44
   231.2  678.89   260.1  677.01   289.0  674.92   317.9  672.65   375.7  667.64
   397.1  665.59   412.1  664.21   434.0  662.27   463.6  659.99   493.0  658.83
   522.5  659.58   552.0  661.22   670.0  668.54   788.0  676.15   847.0  679.84
#Mann= 3 , 0 , 0
       0     0.1       0   397.1   0.045       0   412.1     0.1       0
Bank Sta=397.1,412.1
Exp/Cntr=0.3,0.1

Type RM Length L Ch R = 1 ,1933.6,145.7,150,153.5
XS GIS Cut Line= 3
     2218757.192      663904.853     2219137.469      664071.038
     2219511.796      664241.750
#Sta/Elev= 20
       0  691.74    59.3  688.01   118.6  684.39   177.9  680.53   207.5  678.49
   237.1  676.17   266.8  673.60   296.4  670.88   326.1  667.83   385.4  660.55
   407.5  658.30   415.0  657.54   422.5  657.32   444.4  656.66   473.8  657.32
   503.2  658.82   532.6  660.43   591.3  663.83   679.5  669.36   826.4  679.45
#Mann= 3 , 0 , 0
       0     0.1       0   407.5   0.045       0   422.5     0.1       0
Bank Sta=407.5,422.5
Exp/Cntr=0.3,0.1

Type RM Length L Ch R = 1 ,1783.6,156.8,150,145.9
XS GIS Cut Line= 3
     2218728.232      663962.599     2219075.294      664200.302
     2219390.454      664458.947
#Sta/Elev= 24
       0  690.66    56.1  686.65   112.2  682.95   140.2  681.00   196.3  676.84
   224.4  674.38   252.4  671.74   308.5  666.13   336.5  663.14   392.6  656.78
   413.2  655.78   420.7  655.42   428.2  655.58   449.8  656.06   478.9  656.86
   537.2  658.77   566.3  660.03   595.4  661.40   624.5  662.83   682.8  665.91
   711.9  668.07   770.1  672.99   799.2  675.56   828.4  677.98
#Mann= 3 , 0 , 0
       0     0.1       0   413.2   0.045       0   428.2     0.1       0
Bank Sta=413.2,428.2
Exp/Cntr=0.3,0.1

Type RM Length L Ch R = 1 ,1633.6,143.8,150,146.4
XS GIS Cut Line= 3
     2218587.714      664190.928     2218977.291      664311.055
     2219346.964      664514.479
#Sta/Elev= 27
       0  681.32    29.1  680.11   116.5  676.89   174.7  674.54   203.8  673.15
   233.0  671.41   262.1  669.18   291.2  666.45   320.3  663.60   349.4  660.60
   378.6  657.15   400.2  655.36   407.7  654.74   415.2  654.75   435.8  654.79
   463.9  655.67   520.2  657.07   548.3  657.93   604.6  660.20   632.7  661.43
   660.8  662.76   689.0  664.31   717.1  666.04   745.2  668.01   773.4  670.17
   801.5  672.60   829.6  675.27
#Mann= 3 , 0 , 0
       0     0.1       0   400.2   0.045       0   415.2     0.1       0
Bank Sta=400.2,415.2
Exp/Cntr=0.3,0.1

Type RM Length L Ch R = 1 ,1483.6,143.8,150,158.7
XS GIS Cut Line= 3
     2218569.212      664231.371     2218921.206      664447.215
     2219311.547      664590.435
#Sta/Elev= 25
       0  679.10    29.5  677.81    59.0  676.80    88.5  675.61   118.0  674.26
   177.0  671.27   206.4  669.64   235.9  667.55   265.4  665.10   353.9  657.17
   383.4  654.42   405.4  653.08   412.9  652.62   420.4  652.77   442.6  653.22
   502.0  655.40   561.4  657.81   620.8  660.37   650.5  661.82   680.2  663.48
   709.9  665.41   739.6  667.88   769.3  670.67   799.0  673.62   828.7  676.68
#Mann= 3 , 0 , 0
       0     0.1       0   405.4   0.045       0   420.4     0.1       0
Bank Sta=405.4,420.4
Exp/Cntr=0.3,0.1

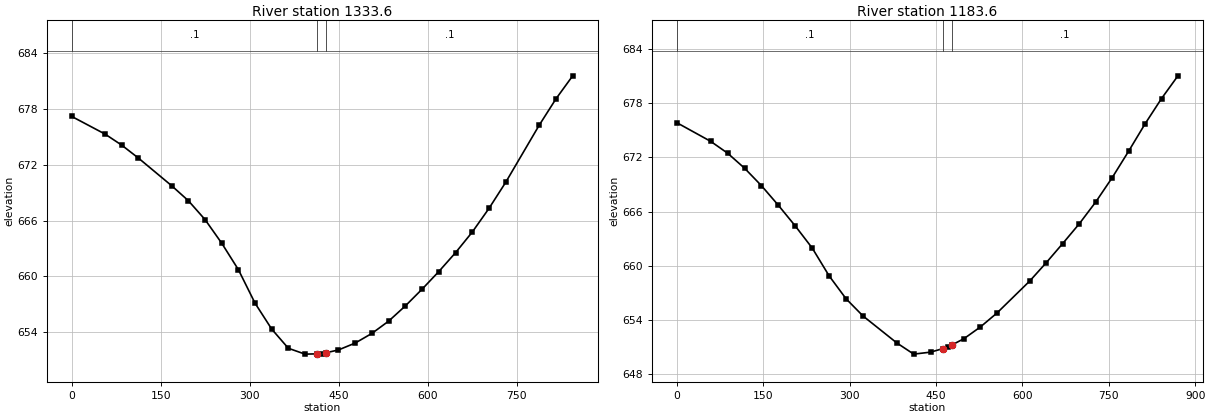
Type RM Length L Ch R = 1 ,1333.6,142.8,150,144.2
XS GIS Cut Line= 3
     2218547.413      664264.810     2218849.167      664558.842
     2219158.165      664847.733
#Sta/Elev= 30
       0  677.21    56.2  675.31    84.3  674.12   112.4  672.73   168.5  669.75
   196.6  668.14   224.7  666.11   252.8  663.57   280.9  660.72   309.0  657.11
   337.1  654.32   365.1  652.26   393.2  651.63   413.8  651.66   421.3  651.67
   428.8  651.78   449.5  652.08   477.7  652.82   505.9  653.86   534.1  655.18
   562.3  656.82   590.5  658.62   618.7  660.52   646.9  662.55   675.1  664.77
   703.3  667.32   731.5  670.13   787.9  676.27   816.1  679.10   844.3  681.58
#Mann= 3 , 0 , 0
       0     0.1       0   413.8   0.045       0   428.8     0.1       0
Bank Sta=413.8,428.8
Exp/Cntr=0.3,0.1

Type RM Length L Ch R = 1 ,1183.6,1154.4,1183.6,1218.9
XS GIS Cut Line= 3
     2218519.690      664294.722     2218776.396      664688.322
     2219126.992      664881.362
#Sta/Elev= 30
       0  675.82    58.7  673.76    88.1  672.45   117.5  670.79   146.8  668.86
   176.2  666.69   205.6  664.40   235.0  661.96   264.3  658.89   293.7  656.36
   323.1  654.46   381.8  651.48   411.2  650.24   440.5  650.46   462.4  650.86
   469.9  651.00   477.4  651.25   498.5  651.95   527.1  653.25   555.7  654.78
   612.8  658.33   641.4  660.35   670.0  662.47   698.6  664.64   727.2  667.05
   755.8  669.74   784.4  672.67   813.0  675.70   841.6  678.50   870.1  681.01
#Mann= 3 , 0 , 0
       0     0.1       0   462.4   0.045       0   477.4     0.1       0
Bank Sta=462.4,477.4
Exp/Cntr=0.3,0.1