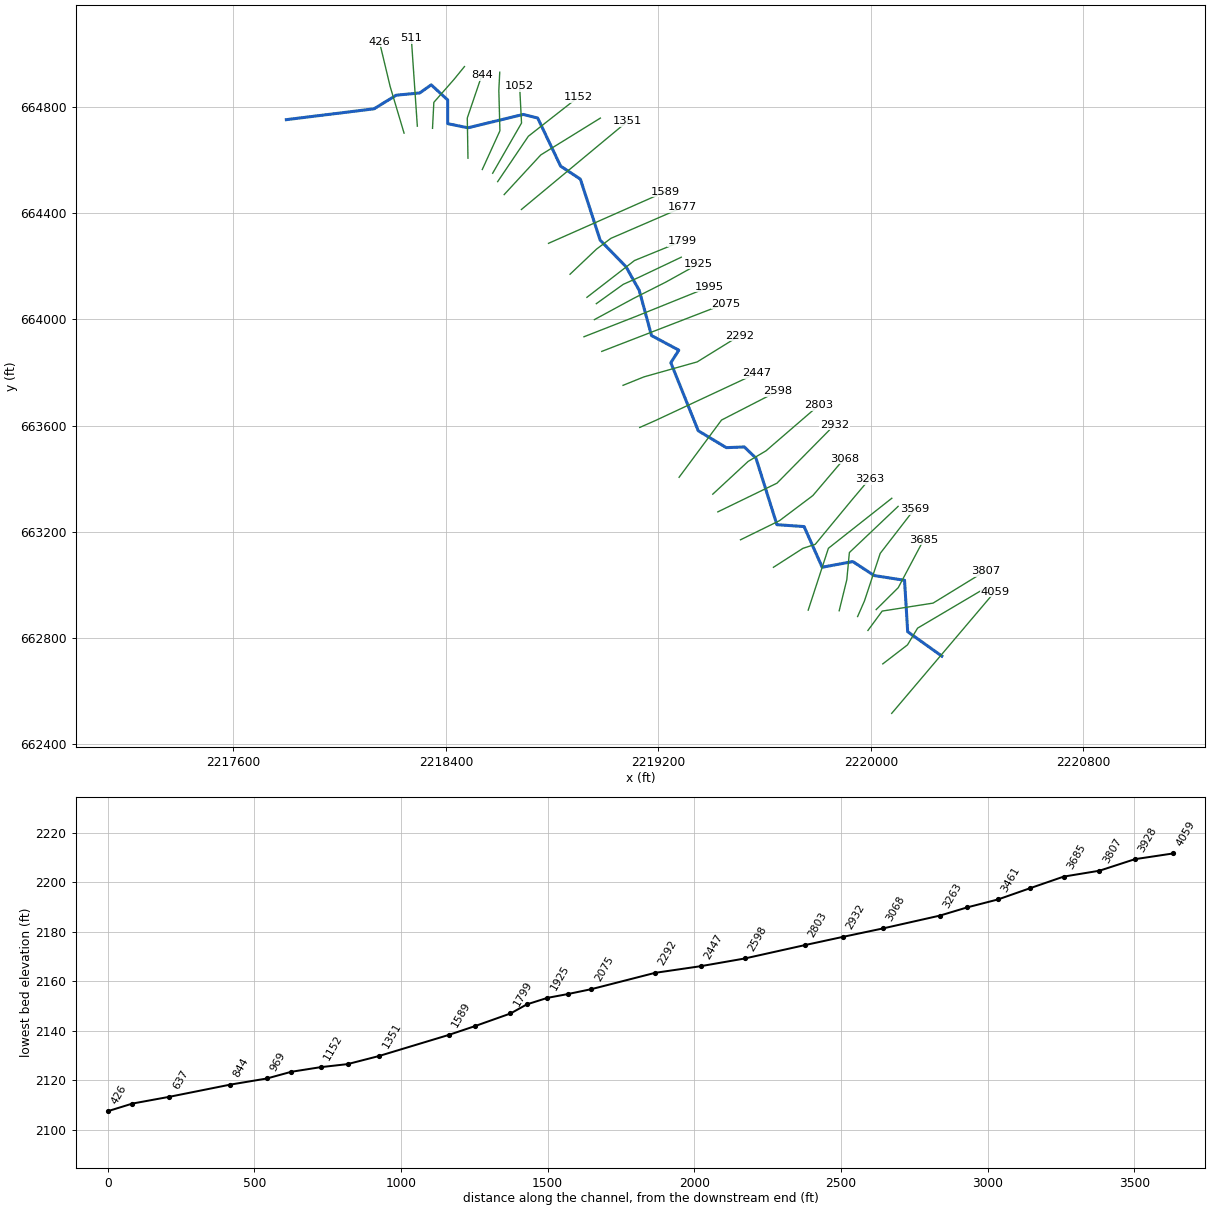
--- JENKSFKT1.prj (project) ---

Proj Title=JENKSFKT1
Current Plan=p01
Default Exp/Contr=0.3,0.1
English Units
Geom File=g01
Flow File=f01
Plan File=p01
Y Axis Title=Elevation
X Axis Title(PF)=Main Channel Distance
X Axis Title(XS)=Station
BEGIN DESCRIPTION:
---------- MODELED AS PART OF WVEMD CTP PROGRAM, 2023----------
Stream Name:Jenks Fork Tributary 1
Flood Zone:  AFH
Upshur County, WV
HEC-RAS Version: RAS 6.3
Vertical Datum: NAVD88
Projection: NAD 1983 StatePlane West Virginia S FIPS 4702 (US Feet)
Terrain: 1-meter LIDAR (FEMA Region III 3DEP collected 2016-2018)
Land Use: 2019 NLCD
Hydrologic Method:
WV SIR2010-5033 regression equations
Additional Model Notes:
None
END DESCRIPTION:
DSS File=dss
DSS Export Rating Curves= 0
DSS Export Rating Curve Sorted= 0
DSS Export Volume Flow Curves= 0
DXF Filename=JENKSFKT.
DXF OffsetX= 0
DXF OffsetY= 0
DXF ScaleX= 1
DXF ScaleY= 10

--- JENKSFKT1.p01 (plan) ---

Plan Title=Floodplain
Program Version=6.30
Short Identifier=Floodplain
Geom File=g01
Flow File=f01
Subcritical Flow
K Sum by GR= 0
Std Step Tol= 0.01
Critical Tol= 0.01
Num of Std Step Trials= 20
Max Error Tol= 0.3
Flow Tol Ratio= 0.001
Split Flow NTrial= 30
Split Flow Tol= 0.02
Split Flow Ratio= 0.02
Log Output Level= 0
Friction Slope Method= 1
Unsteady Friction Slope Method= 2
Unsteady Bridges Friction Slope Method= 1
Parabolic Critical Depth
Global Vel Dist= 0 , 0 , 0
Global Log Level= 0
CheckData=True
Encroach Param=-1 ,0,0, 0
Computation Interval=1MIN
Output Interval=1HOUR
Instantaneous Interval=1HOUR
Mapping Interval=1HOUR
Computation Time Step Use Courant=        0
Computation Time Step Use Time Series=    0
Computation Time Step Count To Double=0
Computation Time Step Max Doubling=0
Computation Time Step Max Halving=0
Computation Time Step Residence Courant=0
Run HTab= 0
Run UNet= 0
Run Sediment= 0
Run PostProcess= 0
Run WQNet= 0
Run RASMapper=-1
UNET Theta= 1
UNET Theta Warmup= 1
UNET ZTol= 0.02
UNET ZSATol= 0.02
UNET MxIter= 20
UNET Max Iter WO Improvement= 0
UNET MaxInSteps= 0
UNET DtIC= 0
UNET DtMin= 0
UNET MaxCRTS= 20
UNET WFStab= 2
UNET SFStab= 1
UNET WFX= 1
UNET SFX= 1
UNET Gravity=32.17405
UNET 1D Methodology=Finite Difference
UNET DSS MLevel= 4
UNET Pardiso=0
UNET DZMax Abort= 100
UNET Use Existing IB Tables=-1
UNET Froude Reduction=False
UNET Froude Limit= 0.8
UNET Froude Power= 4
UNET D1 Cores= 0
UNET WindReference=Eulerian
UNET WindDragFormulation=Hsu (1988)
UNET D2 Coriolis=0
UNET D2 Cores= 0
UNET D2 Theta= 1
UNET D2 Theta Warmup= 1
UNET D2 Z Tol= 0.01
UNET D2 Volume Tol= 0.01
UNET D2 Max Iterations= 20
UNET D2 Equation= 0
UNET D2 RampUpFraction=0.1
UNET D2 TimeSlices= 1
UNET D2 Turbulence Formulation=None
UNET D2 Eddy Viscosity=0.3
UNET D2 Transverse Eddy Viscosity=0.1
UNET D2 Smagorinsky Mixing=0.05
UNET D2 BCVolumeCheck=0
UNET D2 Cores=0
UNET D2 SolverType=PARDISO (Direct)
UNET D2 Minimum Iterations= 3
UNET D2 Maximum Iterations= 30
UNET D2 Restart Number= 10
UNET D2 Relaxation Coeff=1.3
UNET D2 SOR Precondition Iterations= 10
UNET D2 ILUT Maximum Fill= 8
UNET D2 ILUT Tolerance=1E-08
UNET D2 Convergence Tolerance=0.00001
UNET D1D2 MaxIter= 0
UNET D1D2 ZTol=0.01
UNET D1D2 QTol=0.1
UNET D1D2 MinQTol=1
DSS File=dss
Write IC File= 0
Write IC File at Fixed DateTime=0
Write IC File at Sim End=0
Echo Input=False
Echo Parameters=False
Echo Output=False
Write Detailed= 0
HDF Write Warmup=0
HDF Write Time Slices=0
HDF Flush=0
HDF Compression= 1
HDF Chunk Size= 1
HDF Spatial Parts= 1
HDF Use Max Rows=0
HDF Fixed Rows= 1
Calibration Method= 0
Calibration Iterations= 20
Calibration Max Change=0.05
Calibration Tolerance=0.2
Calibration Maximum=1.5
Calibration Minimum=0.5
Calibration Optimization Method= 1
WQ AD Non Conservative
WQ ULTIMATE=-1
WQ Max Comp Step=1HOUR
WQ Output Interval=15MIN
WQ Output Selected Increments= 0
WQ Output face flow=0
WQ Output face velocity=0
WQ Output face area=0
WQ Output face dispersion=0
WQ Output cell volume=0
WQ Output cell surface area=0
WQ Output cell continuity=0
WQ Output cumulative cell continuity=0
WQ Output face conc=0
WQ Output face dconc_dx=0
WQ Output face courant=0
WQ Output face peclet=0
WQ Output face adv mass=0
WQ Output face disp mass=0
WQ Output cell mass=0
WQ Output cell source sink temp=0
WQ Output nsm pathways=0
WQ Output nsm derived pathways=0
WQ Create Restart=0
WQ Fixed Restart=0
WQ System Summary=0
WQ Write To DSS=0
Sorting and Armoring Iterations= 10
XS Update Threshold= 0.02
Bed Roughness Predictor= 0
Hydraulics Update Threshold= 0.02
Energy Slope Method= 1
Volume Change Method= 1
Sediment Retention Method= 0
Sediment TS Multiplier= 1
Warm Up Method= 0
XS Weighting Method= 0
Number of US Weighted Cross Sections= 1
Number of DS Weighted Cross Sections= 1
Upstream XS Weight=0
Main XS Weight=1
Downstream XS Weight=0
Number of DS XS's Weighted with US Boundary= 1
Upstream Boundary Weight= 1
Weight of XSs Associated with US Boundary= 0
Number of US XS's Weighted with DS Boundary= 1
Downstream Boundary Weight= 0.5
Weight of XSs Associated with DS Boundary= 0.5
Percentile Method= 0
Sediment Output Level= 3
Mass or Volume Output= 0
Output Increment Type= 1
Profile and TS Output Increment= 1
Transport Output Increment 1
XS Output Flag= 0
XS Output Increment= 10
Read HDF5 Sediment Hotstart= 0
Sediment Hotstart Type= 0
Write Gradation File= 0
Read Gradation Hotstart= 0
Write HDF5 File= 1
Write Binary Output= 1
Write DSS Sediment File= 0
DSS Sediment Output Type= 1
SV Curve= 0
Specific Gage Flag= 0
Subcell Erosion Methods= 0
Subcell Deposition Methods= 0
Advection Scheme= 1
Matrix Solver= 0
Implicit Weighting Factor= 1
Maximum Outer Loop Convergence Iterations= 5
Convergence Maximum Absolute= 0.001
Convergence RMSE= 0.0001
Grain Fractions Max Abs Error= 0.001
Max Subgrid Regions= 1
Max Subgrid Length Scale= 3.402823E+38
Initial Layer Thickness= 3.402823E+38
Min Layer Thickness= 3.402823E+38
Max Layer Thickness= 3.402823E+38
Number of Layers= 5

--- JENKSFKT1.f01 (steady flow) ---

Flow Title=Flows
Program Version=6.30
Number of Profiles= 1
Profile Names=01pct
River Rch & RM=River,Reach,4059
     358
Boundary for River Rch & Prof#=River,Reach           , 1
Up Type= 0
Dn Type= 3
Dn Slope=0.025
DSS Import GetInterval= 0
DSS Import GetPeak= 0
DSS Import FillOption= 0

--- JENKSFKT1.g01 (geometry) ---

Geom Title=Geometry
Program Version=6.30

River Reach=River           ,Reach
Reach XY= 30
2220267.20701408662731.6424459212220138.57636584662823.443771508
2220126.72927667663017.140809374 2220012.4926285663035.004700078
2219932.02492848663087.6302718172219816.61342709 663066.31106792
2219748.50627984663219.4659453292219646.14559217663226.505629411
2219567.40734549663476.891621448 2219523.5148704663519.227124618
2219455.76061423663516.5829150822219349.96606642663580.175525759
2219246.77532792 663836.206181672219276.76509734663883.709367501
2219173.94640534663938.7102417452219127.76929094 664108.86321049
2219077.62376334664198.2894470082218980.61411484664297.903092922
2218906.12574675664527.6355730912218831.66592193664576.712574679
2218745.35900792664757.7971862492218690.95943296664771.277975056
2218482.63184309664720.9678635932218406.48370142664736.621047515
2218406.41044374664825.9390171372218344.41608522664882.696434769
2218301.11809851664852.145422763 2218212.6934066664843.674967255
 2218129.3625365664792.4801877642217798.95772754664751.616145359

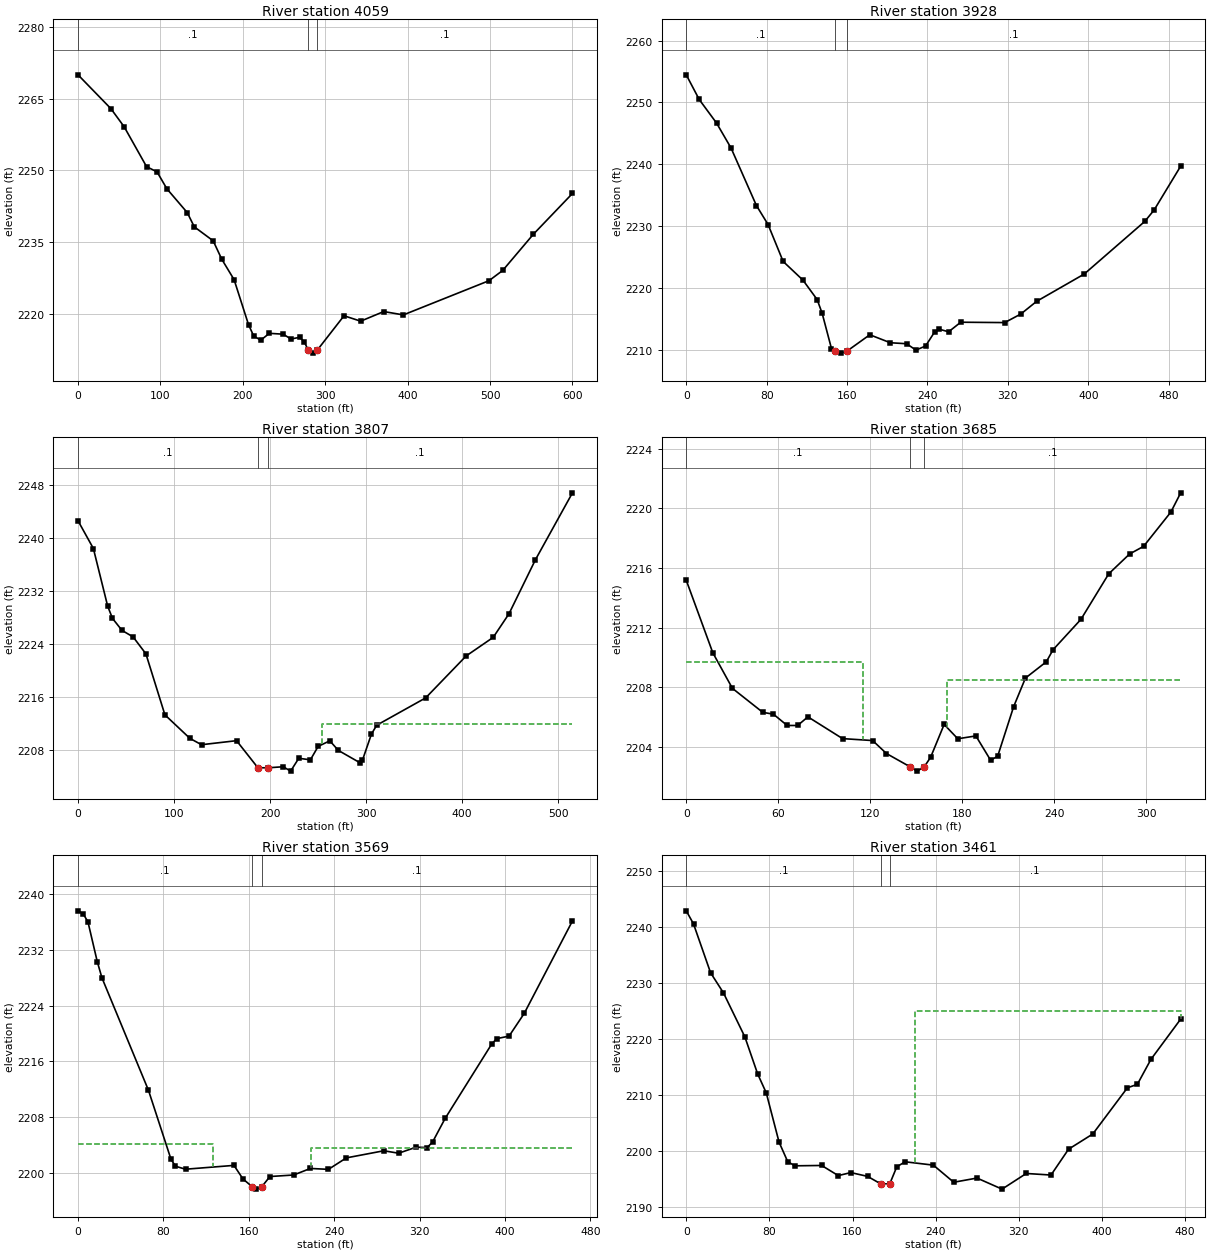
Type RM Length L Ch R = 1 ,4059    ,131.3,131.3,131.3
XS GIS Cut Line= 2
2220078.39279513662516.047840812  2220466.383132662973.719664818
#Sta/Elev= 30
       0 2269.95    39.9 2262.88      56 2259.09    83.2 2250.75    95.9 2249.66
   107.9 2246.11   132.6 2241.14   141.1 2238.17     164 2235.25   174.5 2231.38
   189.4 2227.13   206.9 2217.73   213.1 2215.38   221.7 2214.47   232.2 2215.91
     249 2215.73   258.4 2214.72   268.8 2215.07   274.5 2214.15   279.4 2212.39
   284.7 2211.77   290.22212.369   322.8 2219.58     343 2218.45     371 2220.46
   394.8 2219.76   498.7 2226.91   515.4 2229.06   552.6 2236.63     600 2245.15
#Mann= 3 ,-1,0
       0      .1       0   279.4    .045       0   290.2      .1       0
Bank Sta=279.4,290.2
XS Rating Curve= 0 ,0
Exp/Cntr(USF)=0,0
Exp/Cntr=0.3,0.1

Type RM Length L Ch R = 1 ,3928    ,121.1,121.1,121.1
XS GIS Cut Line= 4
2220044.82653388 662702.384204242220137.86716672662773.953921807
2220175.79911703662836.9352732662220434.88149462 662990.09446886
#Sta/Elev= 30
       0 2254.46    12.9 2250.47    30.1 2246.67    44.6 2242.61    69.8 2233.32
    81.4 2230.24    96.4 2224.27   116.1 2221.25   130.2 2218.11   135.2 2215.89
   144.5 2210.16   147.6 2209.75   153.5 2209.44   159.7 2209.74   182.6 2212.41
     203 2211.12   219.2 2210.96   228.5 2209.93   238.1 2210.59   247.1 2212.87
   251.7 2213.31     261 2212.89   273.1 2214.44   316.8 2214.38   332.9 2215.77
   348.6 2217.82   395.9 2222.23   456.2 2230.75   465.5  2232.6   491.9 2239.69
#Mann= 3 ,-1,0
       0      .1       0   147.6    .045       0   159.7      .1       0
Bank Sta=147.6,159.7
XS Rating Curve= 0 ,0
Exp/Cntr(USF)=0,0
Exp/Cntr=0.3,0.1

Type RM Length L Ch R = 1 ,3807    ,121.8,121.8,121.8
XS GIS Cut Line= 4
2219988.88242906662828.2693841142220042.57566252662901.209120517
2220234.15978064662931.2615312022220430.54568866663051.792125449
#Sta/Elev= 30
       0 2242.58      16 2238.39    30.9 2229.67    35.9 2227.83    45.8 2226.02
    57.4 2225.03    70.7 2222.48    90.5 2213.26   116.5 2209.71   128.6 2208.75
   165.1 2209.36   187.32205.274   197.5 2205.26   213.7 2205.42   221.4 2204.76
   229.9  2206.7     242 2206.47   250.1  2208.5   262.2 2209.34   271.1 2207.89
   293.2 2206.06   296.2 2206.41   305.6 2210.37   311.1  2211.7     362 2215.82
   404.2 2222.16   432.4 2224.97   448.8 2228.53   476.4 2236.71   514.9  2246.8
#Mann= 3 ,-1,0
       0      .1       0   187.3    .045       0   197.5      .1       0
#XS Ineff= 1 ,-1
254.5292514.8782 2211.93
Permanent Ineff=
       T
Bank Sta=187.3,197.5
XS Rating Curve= 0 ,0
Exp/Cntr(USF)=0,0
Exp/Cntr=0.3,0.1

Type RM Length L Ch R = 1 ,3685    ,115.9,115.9,115.9
XS GIS Cut Line= 3
2220019.88227512662906.8543051062220103.06500005662989.420861703
2220199.18725997663170.574351552
#Sta/Elev= 30
       0 2215.18    17.3 2210.32    30.1 2207.93    49.9 2206.32    56.8  2206.2
    65.8 2205.44    72.6 2205.44    79.3 2206.02   101.9 2204.56   121.5 2204.43
   130.5 2203.56   145.82202.677   150.4 2202.38     155 2202.65   159.3 2203.31
   168.1 2205.51     177 2204.55   188.8 2204.74   198.4 2203.11     203 2203.38
   213.4  2206.7   221.1 2208.62   234.7 2209.71   239.1 2210.52   257.3 2212.56
   275.4 2215.61     289 2216.94   298.1 2217.45   315.9 2219.75   322.3 2221.04
#Mann= 3 ,-1,0
       0      .1       0   145.8    .045       0     155      .1       0
#XS Ineff= 2 , 0
          114.99 2209.72  170.02         2208.46
Permanent Ineff=
       F       F
Bank Sta=145.8,155
XS Rating Curve= 0 ,0
Exp/Cntr(USF)=0,0
Exp/Cntr=0.3,0.1

Type RM Length L Ch R = 1 ,3569    ,107.9,107.9,107.9
XS GIS Cut Line= 4
2219950.06382409662880.6436924032219975.94289407662939.795852353
2220035.09505402 663118.484668872220163.82103902663284.875567397
#Sta/Elev= 30
       0 2237.61       5 2237.14     9.3 2236.03      18 2230.33    22.4 2227.99
      66 2211.83    87.1 2201.92    91.3 2200.92   100.7 2200.49   146.1 2201.04
   154.6 2199.08   163.22197.977   167.1 2197.63   172.12197.967   179.8 2199.44
     202 2199.66   217.7  2200.6   234.6 2200.47   251.4 2202.12   286.5 2203.14
   300.3 2202.79   316.9 2203.66     327  2203.6   332.1 2204.38   343.9 2207.78
   387.7 2218.51   392.3 2219.25   403.8 2219.61     418 2222.87   463.2 2236.16
#Mann= 3 ,-1,0
       0      .1       0   163.2    .045       0   172.1      .1       0
#XS Ineff= 2 , 0
        126.2102 2204.13  217.92         2203.58
Permanent Ineff=
       T       F
Bank Sta=163.2,172.1
XS Rating Curve= 0 ,0
Exp/Cntr(USF)=0,0
Exp/Cntr=0.3,0.1

Type RM Length L Ch R = 1 ,3461    ,104.5,104.5,104.5
XS GIS Cut Line= 4
 2219880.6282319662902.428711977 2219909.3827541663019.500695213
2219918.96759483663121.5107858682220102.44883171663295.407182019
#Sta/Elev= 30
       0 2242.91       7 2240.57    23.4 2231.84    35.8 2228.24    56.4 2220.37
    68.7 2213.75      77 2210.35    89.3 2201.55    97.6 2198.07   104.4 2197.31
   130.3 2197.37   146.3 2195.56   158.4  2196.1   174.5 2195.42   187.1 2194.09
   195.82194.076   202.6 2197.13   210.6 2198.03   237.8 2197.43   257.4 2194.37
   279.8 2195.12   303.9 2193.14   327.2 2195.94     351 2195.66   367.9 2200.28
   391.2    2203   424.5 2211.26   434.1 2211.88   447.2 2216.36   475.8 2223.55
#Mann= 3 ,-1,0
       0      .1       0   187.1    .045       0   195.8      .1       0
#XS Ineff= 2 , 0
                          219.96         2225.02
Permanent Ineff=
       F       F
Bank Sta=187.1,195.8
XS Rating Curve= 0 ,0
Exp/Cntr(USF)=0,0
Exp/Cntr=0.3,0.1

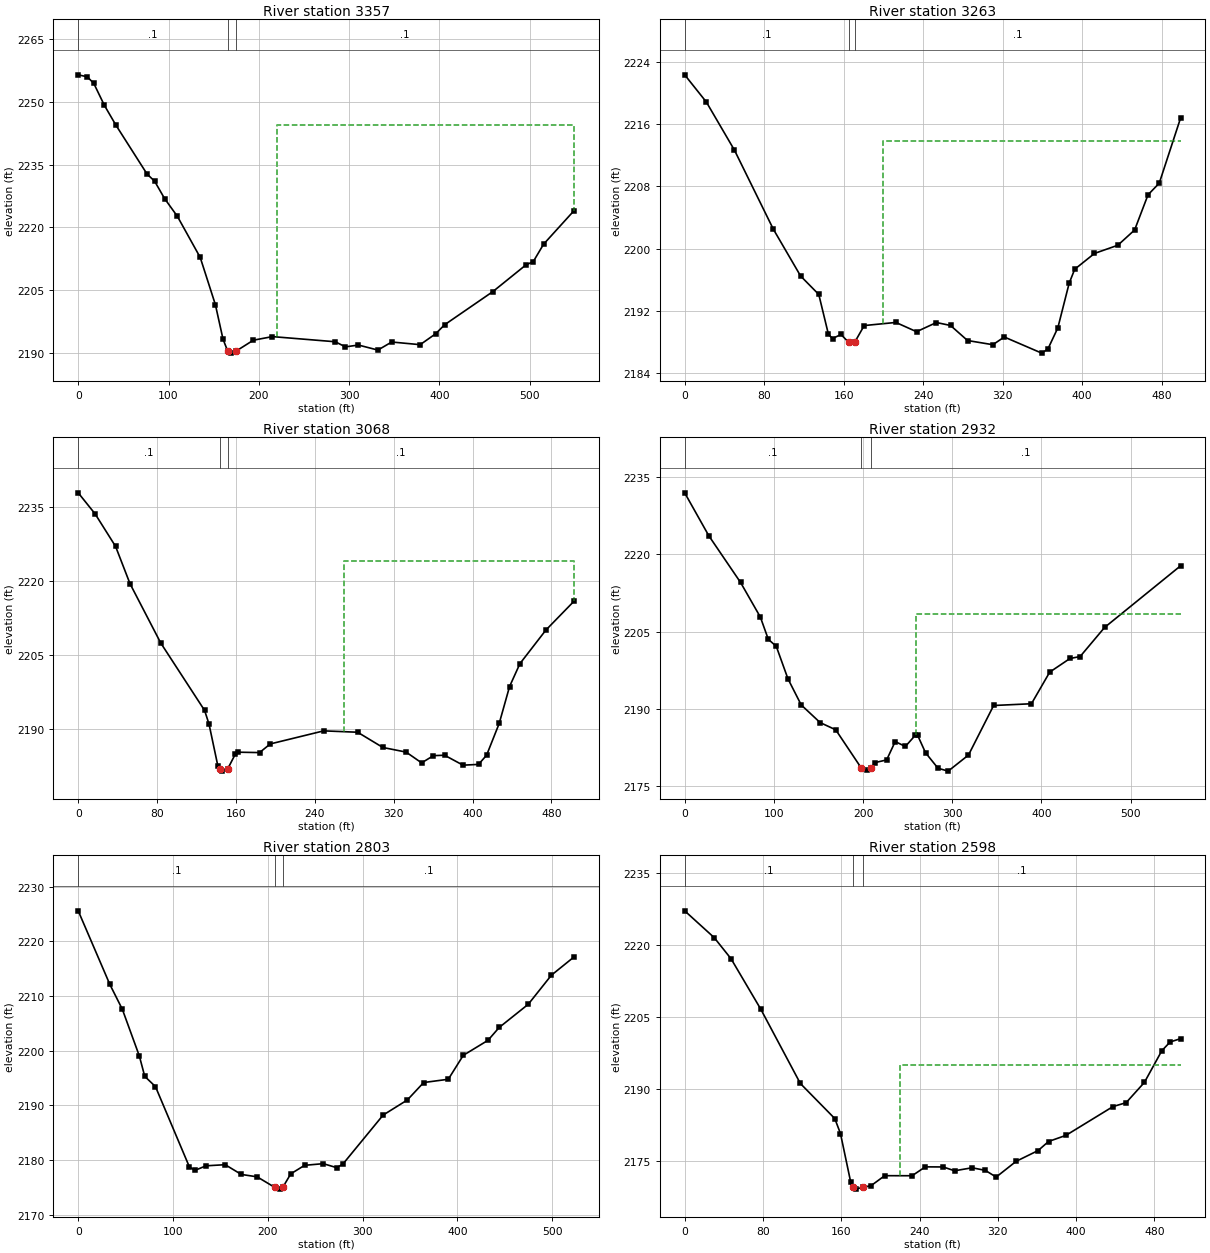
Type RM Length L Ch R = 1 ,3357    ,93.9,93.9,93.9
XS GIS Cut Line= 3
2219763.96341365662904.782910048 2219840.0335782663137.689092853
2220078.75373399663326.065079689
#Sta/Elev= 30
       0 2256.49      10 2256.02    17.2 2254.46      29 2249.18    41.7 2244.47
    76.2 2232.77    84.6 2231.05    95.6 2226.91   109.8 2222.65   135.1 2212.81
   151.9 2201.51   160.3  2193.3   165.4 2190.48   168.7 2189.94   174.9 2190.44
   193.9 2193.03     215 2193.89   284.6 2192.66   295.8 2191.44   310.3 2191.87
   331.8 2190.67   347.1  2192.6   378.6 2191.96   395.7 2194.56   405.6 2196.71
   459.2 2204.67   495.4 2210.98   503.9 2211.85   515.3    2216   549.1 2224.04
#Mann= 3 ,-1,0
       0      .1       0   165.4    .045       0   174.9      .1       0
#XS Ineff= 2 , 0
                          219.89         2244.39
Permanent Ineff=
       F       F
Bank Sta=165.4,174.9
XS Rating Curve= 0 ,0
Exp/Cntr(USF)=0,0
Exp/Cntr=0.3,0.1

Type RM Length L Ch R = 1 ,3263    ,194.9,194.9,194.9
XS GIS Cut Line= 5
2219633.09157177663066.0892927582219744.23329426 663137.49104043
2219790.44591922663152.5529330112219928.05684689 663319.26069862
2219994.06276356663397.479729741
#Sta/Elev= 30
       0 2222.32    21.8 2218.83    50.1 2212.65    89.2 2202.51   116.7 2196.49
     135 2194.12   144.7    2189   148.9 2188.46   157.3 2188.99   164.92187.996
   171.22187.998   180.7 2190.13   212.6 2190.53   233.4 2189.34   253.4 2190.52
   267.6 2190.14   284.7 2188.21   310.2 2187.67   321.7 2188.66   359.4 2186.59
   365.6 2187.12   375.6 2189.83     387 2195.56   392.6 2197.36   412.5 2199.39
     436 2200.44   452.9  2202.4   466.4 2206.92   477.7 2208.41   499.2 2216.79
#Mann= 3 ,-1,0
       0      .1       0   164.9    .045       0   171.2      .1       0
#XS Ineff= 2 , 0
                          199.44         2213.84
Permanent Ineff=
       F       F
Bank Sta=164.9,171.2
XS Rating Curve= 0 ,0
Exp/Cntr(USF)=0,0
Exp/Cntr=0.3,0.1

Type RM Length L Ch R = 1 ,3068    ,136.2,136.2,136.2
XS GIS Cut Line= 4
2219509.05876423663169.6167742512219656.07355921663241.734393321
2219781.46147115663336.1625857762219899.48643569663475.050918995
#Sta/Elev= 30
       0 2237.98    17.2 2233.68    37.9 2227.08    52.5 2219.51    83.7 2207.44
   128.2 2193.72   132.7 2190.92   141.6 2182.47   143.82181.822     146 2181.38
   151.5 2181.79   159.4 2184.86   162.5 2185.23   183.9 2185.15   194.8 2186.91
     249 2189.57   283.4 2189.29     309 2186.19   332.6 2185.25   348.3 2183.06
   360.3 2184.53   371.6 2184.61   390.3 2182.59     406 2182.75   414.2 2184.62
     427 2191.09   437.5 2198.59     448 2203.24   474.3 2210.06     503 2215.97
#Mann= 3 ,-1,0
       0      .1       0   143.8    .045       0   151.5      .1       0
#XS Ineff= 2 , 0
                          270.04         2224.09
Permanent Ineff=
       F       F
Bank Sta=143.8,151.5
XS Rating Curve= 0 ,0
Exp/Cntr(USF)=0,0
Exp/Cntr=0.3,0.1

Type RM Length L Ch R = 1 ,2932    ,128.4,128.4,128.4
XS GIS Cut Line= 3
2219423.80536417663274.8449497912219646.38103081663382.845800689
2219863.32187044 663602.60405382
#Sta/Elev= 30
       0 2231.91    27.1 2223.58    62.7 2214.53    84.9 2207.82    93.8 2203.51
   102.7 2202.17   115.8 2195.87   130.7  2190.8   151.9 2187.38   169.4 2185.98
   197.8 2178.64   204.9  2178.1   208.6 2178.59   213.8 2179.64   226.5 2180.14
   236.1  2183.7   247.5 2182.75   258.8 2184.95   261.3  2184.9   270.1 2181.54
   284.1 2178.53   295.5 2177.97   318.3 2181.09   346.5 2190.69   388.9 2191.03
   409.4 2197.16   432.1  2199.8   443.5 2200.18   470.9 2205.81   556.2 2217.77
#Mann= 3 ,-1,0
       0      .1       0   197.8    .045       0   208.6      .1       0
#XS Ineff= 2 , 0
                          259.94         2208.43
Permanent Ineff=
       F       F
Bank Sta=197.8,208.6
XS Rating Curve= 0 ,0
Exp/Cntr(USF)=0,0
Exp/Cntr=0.3,0.1

Type RM Length L Ch R = 1 ,2803    ,205.5,205.5,205.5
XS GIS Cut Line= 4
2219404.72351167663341.4882486052219537.76266318663464.736913911
2219605.04161164663504.616490352 2219804.7809756663676.878092431
#Sta/Elev= 30
       0 2225.61    33.4 2212.13    46.6 2207.57    64.5 2199.04    70.2 2195.31
    81.5 2193.44   117.3 2178.74   123.1  2178.1   134.9 2178.94   155.1 2179.14
   172.1 2177.36   188.8 2176.92   207.4 2174.99   212.6 2174.67   215.92175.011
   224.3 2177.47   238.9 2179.03   258.6 2179.33   272.7  2178.6   279.2 2179.24
   321.7 2188.22   347.3 2190.99   364.5 2194.18   390.5 2194.78   406.3 2199.16
   432.4 2201.91   444.2 2204.26   474.9 2208.51   499.3 2213.83   523.3 2217.19
#Mann= 3 ,-1,0
       0      .1       0   207.4    .045       0   215.9      .1       0
Bank Sta=207.4,215.9
XS Rating Curve= 0 ,0
Exp/Cntr(USF)=0,0
Exp/Cntr=0.3,0.1

Type RM Length L Ch R = 1 ,2598    ,150.4,150.4,150.4
XS GIS Cut Line= 3
2219277.78089647 663404.939114852219437.52824202663620.471247729
2219649.67947869663729.505150244
#Sta/Elev= 30
       0 2227.22    30.2 2221.63    47.4 2217.23    77.9 2206.68   118.2 2191.25
   153.4 2183.94   159.2 2180.82   169.6 2170.76     172 2169.59   174.6 2169.24
     182 2169.61   190.6 2169.98   204.4 2172.04   232.4 2172.03   245.9 2173.88
   264.2 2173.86   275.8 2173.06   293.7 2173.69   307.2 2173.15   318.3 2171.75
   338.7 2175.03   361.2 2177.28   371.8 2179.16   389.6 2180.44   437.7 2186.44
   451.1 2187.25   469.8 2191.48   487.6 2198.08   496.1  2199.9   506.8 2200.59
#Mann= 3 ,-1,0
       0      .1       0     172    .045       0     182      .1       0
#XS Ineff= 2 , 0
                          219.91         2195.02
Permanent Ineff=
       F       T
Bank Sta=172,182
XS Rating Curve= 0 ,0
Exp/Cntr(USF)=0,0
Exp/Cntr=0.3,0.1

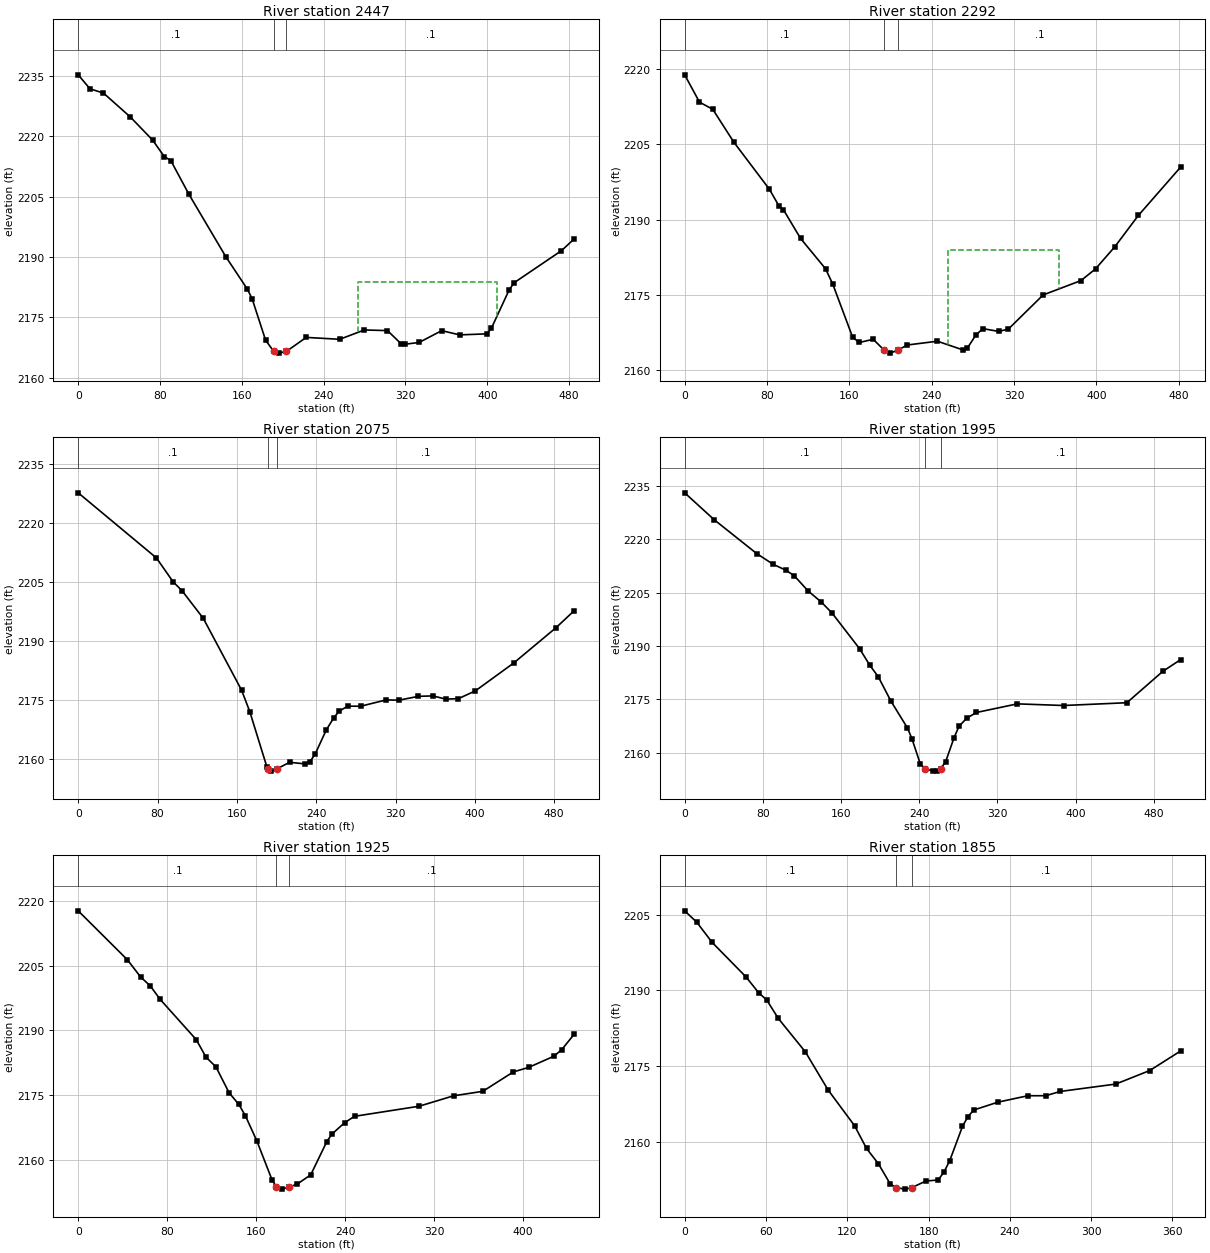
Type RM Length L Ch R = 1 ,2447    ,155.3,155.3,155.3
XS GIS Cut Line= 3
2219129.61676618663592.6023003022219187.09200161663617.959021817
 2219569.5219335663796.446709531
#Sta/Elev= 30
       0 2235.32    11.5 2231.84    24.7 2230.78    50.9 2224.85    72.8 2219.08
    84.1 2215.01    90.5 2214.01   108.3 2205.59   144.3  2190.1   165.4 2182.02
     170 2179.67   183.2 2169.34   191.12166.582   196.4 2166.12   203.62166.555
   222.9 2170.03   255.7 2169.56   279.7 2171.88   302.4 2171.72   315.6 2168.47
     320 2168.35   333.3 2168.77   355.4 2171.71   372.9 2170.66   399.5 2170.91
   403.9 2172.26   421.2 2181.76     426 2183.59   472.4 2191.58   484.9  2194.5
#Mann= 3 ,-1,0
       0      .1       0   191.1    .045       0   203.6      .1       0
#XS Ineff= 1 ,-1
273.9858409.1798 2183.91
Permanent Ineff=
       T
Bank Sta=191.1,203.6
XS Rating Curve= 0 ,0
Exp/Cntr(USF)=0,0
Exp/Cntr=0.3,0.1

Type RM Length L Ch R = 1 ,2292    ,216.8,216.8,216.8
XS GIS Cut Line= 4
2219066.81839702663751.2638917222219145.93136815663783.213360831
 2219345.9959009663839.5052825942219506.51925883663938.760302731
#Sta/Elev= 30
       0 2218.77    14.4 2213.34    27.3 2211.91    47.8 2205.37    82.4 2195.99
    91.8 2192.63      96 2191.93   112.6 2186.24   136.9  2180.2   143.9 2177.15
   163.3 2166.54   169.8 2165.55   183.2 2166.18   193.72164.042   199.8 2163.43
   207.2 2164.04   216.5 2165.05   245.6  2165.8   270.5 2164.06   274.6 2164.41
     283 2167.04   289.8  2168.3   305.1 2167.75   314.5  2168.2   348.3    2175
   385.1 2177.86   399.2 2180.18     418 2184.59   440.8  2190.8   481.9 2200.42
#Mann= 3 ,-1,0
       0      .1       0   193.7    .045       0   207.2      .1       0
#XS Ineff= 1 ,-1
255.9216363.4769 2183.91
Permanent Ineff=
       T
Bank Sta=193.7,207.2
XS Rating Curve= 0 ,0
Exp/Cntr(USF)=0,0
Exp/Cntr=0.3,0.1

Type RM Length L Ch R = 1 ,2075    ,80.8,80.8,80.8
XS GIS Cut Line= 3
2218986.56941694663879.0260577322219413.32304004664044.098314796
2219453.45188511664058.283925086
#Sta/Elev= 30
       0 2227.65    78.9 2211.08    95.7    2205   104.7 2202.74   126.1 2195.72
   164.7 2177.46     173 2171.99   190.4 2157.79   191.6 2157.46   194.7 2156.84
   200.52157.432   213.2 2159.09     229 2158.67   233.3 2159.11   238.8 2161.12
   250.3 2167.39   257.8 2170.45   263.3 2172.14   271.9 2173.37   284.8 2173.35
   310.5 2174.96   323.4 2174.89   343.1 2175.87   357.7 2175.98   370.6 2175.16
   383.4 2175.28   400.6 2177.28   439.2 2184.36   481.8 2193.33   500.1 2197.65
#Mann= 3 ,-1,0
       0      .1       0   191.6    .045       0   200.5      .1       0
Bank Sta=191.6,200.5
XS Rating Curve= 0 ,0
Exp/Cntr(USF)=0,0
Exp/Cntr=0.3,0.1

Type RM Length L Ch R = 1 ,1995    ,69.3,69.3,69.3
XS GIS Cut Line= 3
 2218919.7176922663934.1768142392219114.85604387664010.535299678
 2219391.2010388664122.042929209
#Sta/Elev= 30
       0 2233.04    30.2 2225.48    73.7 2215.97    90.7 2212.93   103.6 2211.29
   112.2 2209.72   126.2  2205.5     140  2202.3   150.8 2199.26     179 2189.23
   189.5 2184.57   198.1 2181.36     211 2174.54     228 2166.95   232.5 2163.99
   241.2 2156.79   246.4  2155.5   254.1 2154.84   258.4 2154.93   261.8  2155.5
     267 2157.45   275.7 2164.26   280.7 2167.42   288.6 2169.72   298.6 2171.32
   340.4 2173.74   387.8 2173.28   452.5 2174.06   489.2 2182.86   507.5 2186.17
#Mann= 3 ,-1,0
       0      .1       0   246.4    .045       0   261.8      .1       0
Bank Sta=246.4,261.8
XS Rating Curve= 0 ,0
Exp/Cntr(USF)=0,0
Exp/Cntr=0.3,0.1

Type RM Length L Ch R = 1 ,1925    ,70.6,70.6,70.6
XS GIS Cut Line= 4
2218958.89664152663998.6537059772219105.54470473 664078.13942091
2219227.54603463664139.7562541922219352.01203786664208.767107468
#Sta/Elev= 30
       0 2217.67    44.1 2206.38    56.1 2202.37    64.8 2200.31    73.6 2197.21
   106.1 2187.88   114.9 2183.82   123.8 2181.59   135.6  2175.6   144.4  2172.9
   150.3 2170.26   160.7 2164.39   174.2 2155.46   178.22153.808   183.2 2153.31
   189.62153.801   196.6 2154.44     209 2156.61   223.5 2164.32     228 2166.02
   239.5 2168.68   248.4 2170.15   306.4 2172.48   337.4 2174.89   363.7 2175.93
   391.1 2180.41   404.8 2181.45   427.7 2184.06   434.5 2185.53   445.8 2189.12
#Mann= 3 ,-1,0
       0      .1       0   178.2    .045       0   189.6      .1       0
Bank Sta=178.2,189.6
XS Rating Curve= 0 ,0
Exp/Cntr(USF)=0,0
Exp/Cntr=0.3,0.1

Type RM Length L Ch R = 1 ,1855    ,55.4,55.4,55.4
XS GIS Cut Line= 4
2218966.21204776664058.7653856692219067.38536661664131.412392812
 2219127.4807966664158.4173012262219286.08708968664233.726764128
#Sta/Elev= 30
       0 2205.73     8.9 2203.48    20.3 2199.47    45.3 2192.64    54.7 2189.48
    60.5 2188.11    69.1 2184.43    89.1  2177.8   105.8 2170.29   125.4 2163.19
   134.2  2158.7     143 2155.66   151.7 2151.67   156.1 2150.94   162.8 2150.65
   167.52150.934     178 2152.25     187 2152.46   191.2 2153.95   195.6 2156.28
     205 2163.05   208.9 2164.94   213.3  2166.3   231.1 2167.86   253.2 2169.13
   266.5 2169.14   277.1 2169.98   318.1 2171.44   343.2 2174.12     366 2177.99
#Mann= 3 ,-1,0
       0      .1       0   156.1    .045       0   167.5      .1       0
Bank Sta=156.1,167.5
XS Rating Curve= 0 ,0
Exp/Cntr(USF)=0,0
Exp/Cntr=0.3,0.1

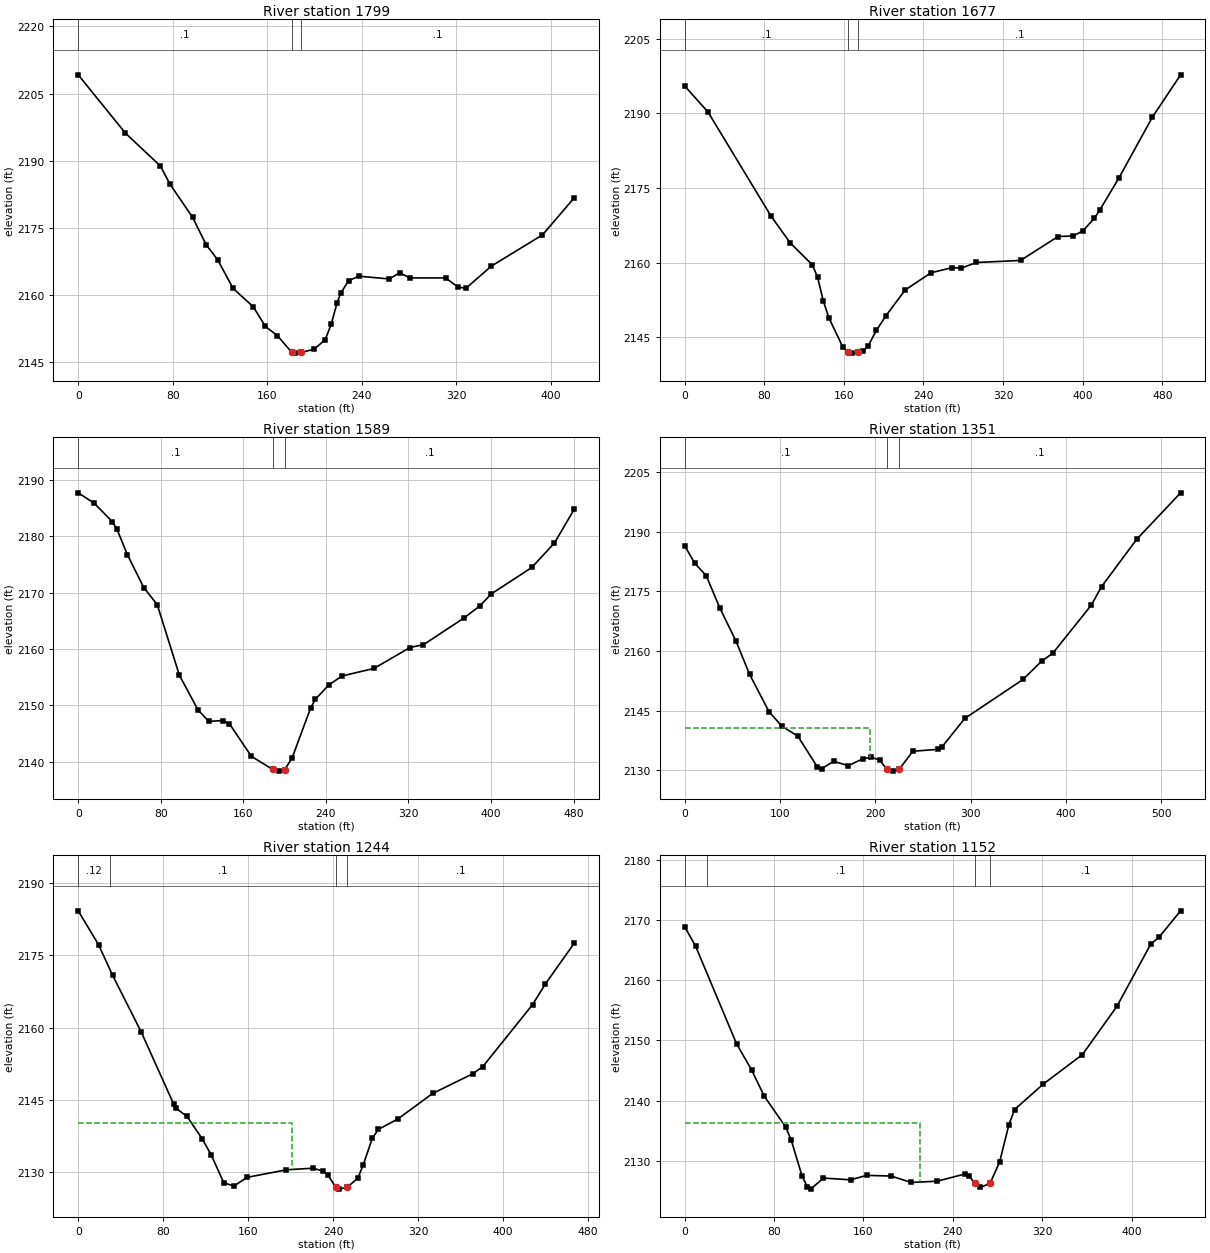
Type RM Length L Ch R = 1 ,1799    ,122.4,122.4,122.4
XS GIS Cut Line= 3
2218930.80455811664082.5774590022219109.92469246664221.215333886
2219289.01057398 664294.30568249
#Sta/Elev= 30
       0 2209.19    39.9 2196.18    69.6  2188.8    77.6  2184.8    96.9 2177.31
   108.3 2171.22   118.1 2167.84   131.1 2161.46   148.2 2157.34   158.5 2152.94
   168.7 2150.87   180.7 2147.18   183.8 2146.98   188.9 2147.18   199.6 2147.82
   209.1 2149.98   214.2 2153.42   219.2 2158.26   222.4 2160.44   228.9 2163.15
   237.4 2164.18   263.5 2163.56   272.1 2164.94   280.8 2163.79     311 2163.79
   321.7 2161.73   328.3 2161.48   349.9 2166.45   393.1 2173.41   419.9 2181.67
#Mann= 3 ,-1,0
       0      .1       0   180.7    .045       0   188.9      .1       0
Bank Sta=180.7,188.9
XS Rating Curve= 0 ,0
Exp/Cntr(USF)=0,0
Exp/Cntr=0.3,0.1

Type RM Length L Ch R = 1 ,1677    ,88.1,88.1,88.1
XS GIS Cut Line= 4
2218867.12688622664169.5345511752218967.30158851664264.491821048
2219021.04114234 664304.666050612219290.26065473664421.014793367
#Sta/Elev= 30
       0 2195.53    23.5 2190.28    86.7 2169.39   106.2 2163.94   128.2 2159.59
   133.5 2157.15   139.2 2152.38   144.9 2148.92   159.1 2142.97   164.1 2142.03
   167.7 2141.82   174.52142.016   179.2 2142.26   184.1 2143.16   192.6 2146.37
     202 2149.26   221.6 2154.52   247.5 2157.97   268.8 2159.01   277.9  2158.9
   293.1 2160.04   337.5 2160.45   375.2 2165.26   390.5 2165.38   400.3 2166.41
   411.8 2168.95   417.4 2170.67   436.1 2176.93     470 2189.25   498.4 2197.77
#Mann= 3 ,-1,0
       0      .1       0   164.1    .045       0   174.5      .1       0
Bank Sta=164.1,174.5
XS Rating Curve= 0 ,0
Exp/Cntr(USF)=0,0
Exp/Cntr=0.3,0.1

Type RM Length L Ch R = 1 ,1589    ,238.3,238.3,238.3
XS GIS Cut Line= 2
2218786.10982101664285.9222553982219225.62632728664480.323787014
#Sta/Elev= 30
       0 2187.69    15.4 2185.86    32.9  2182.6    37.4  2181.3    47.6 2176.74
    63.5 2170.88    76.6 2167.84      98 2155.34   116.2 2149.12   126.7 2147.13
   140.5 2147.28   146.6 2146.69   167.8 2140.93   188.52138.592   194.7  2138.3
   200.22138.587   207.2  2140.6   225.3 2149.55   229.7 2151.02   242.8 2153.59
   255.7 2155.19   286.6 2156.52   321.5 2160.24   334.6 2160.74     374  2165.5
   389.2 2167.62   400.3 2169.75   439.6 2174.45   461.5 2178.79   480.6 2184.75
#Mann= 3 ,-1,0
       0      .1       0   188.5    .045       0   200.2      .1       0
Bank Sta=188.5,200.2
XS Rating Curve= 0 ,0
Exp/Cntr(USF)=0,0
Exp/Cntr=0.3,0.1

Type RM Length L Ch R = 1 ,1351    ,106.6,106.6,106.6
XS GIS Cut Line= 2
2218684.15127215 664413.399201772219084.22398939664745.853994969
#Sta/Elev= 30
       0 2186.52    10.4 2182.15    22.6 2178.97    36.8 2170.86    53.8 2162.51
      68 2154.16    88.4 2144.74   102.1 2141.02   118.6 2138.59     139 2130.87
   143.6 2130.33   156.1 2132.22   171.7 2131.14   187.3 2132.91   195.9 2133.24
   204.4 2132.53   212.22130.205   218.5 2129.75     225  2130.2   239.3 2134.75
   265.3 2135.23   269.7 2135.78   293.8 2143.02   354.9 2152.83   374.5 2157.47
   386.2 2159.45   426.5 2171.54   437.3 2176.22   474.2 2188.15   520.2 2199.83
#Mann= 3 ,-1,0
       0      .1       0   212.2    .045       0     225      .1       0
#XS Ineff= 2 , 0
          194.37  2140.6
Permanent Ineff=
       T       F
Bank Sta=212.2,225
XS Rating Curve= 0 ,0
Exp/Cntr(USF)=0,0
Exp/Cntr=0.3,0.1

Type RM Length L Ch R = 1 ,1244    ,92.2,92.2,92.2
XS GIS Cut Line= 3
2218619.16811387664469.4673661672218757.00608844664618.791838621
 2218981.4345855664757.513389955
#Sta/Elev= 30
       0 2184.23    19.2 2177.18    32.3 2170.89    59.5 2159.02    89.9 2144.13
    92.1 2143.26   102.4 2141.59   116.6 2136.99   125.1 2133.66   137.1 2127.82
   146.6 2127.13     159 2128.93   196.1  2130.5     221 2130.83   230.5 2130.25
   235.2 2129.39   242.6  2126.9   245.8 2126.49   253.4 2126.89   263.4 2128.78
   268.3 2131.43     277 2137.04   282.8 2138.89     301 2141.04   333.9 2146.35
   371.5 2150.41   380.9 2151.87     428 2164.79   439.7 2168.97   467.1 2177.49
#Mann= 4 ,-1,0
       0     .12       0      30      .1       0   242.6    .045       0
   253.4      .1       0
#XS Ineff= 2 , 0
        201.7084 2140.23
Permanent Ineff=
       T       F
Bank Sta=242.6,253.4
XS Rating Curve= 0 ,0
Exp/Cntr(USF)=0,0
Exp/Cntr=0.3,0.1

Type RM Length L Ch R = 1 ,1152    ,99.8,99.8,99.8
XS GIS Cut Line= 3
2218594.69485077664518.1832801422218710.20880434664689.106365911
2218897.09723328664835.611867999
#Sta/Elev= 30
       0 2168.94     9.8 2165.69    46.4 2149.46    59.8 2145.12    71.2 2140.73
    90.5 2135.56    95.3 2133.44     105 2127.46   109.8 2125.62   112.7 2125.25
   124.2 2127.09   148.5  2126.8   162.9 2127.54   184.7 2127.43   202.7 2126.36
   225.9 2126.57   250.5 2127.75   254.5 2127.47   259.6  2126.2   264.7 2125.53
   273.3 2126.23   281.8 2129.75   290.1 2135.95   295.2  2138.5   320.6  2142.7
   355.9 2147.65   386.7 2155.66   417.2 2166.09   424.3 2167.16   443.8 2171.59
#Mann= 4 ,-1,0
       0     .12       0      20      .1       0   259.6    .045       0
   273.3      .1       0
#XS Ineff= 2 , 0
        210.1568 2136.21
Permanent Ineff=
       T       F
Bank Sta=259.6,273.3
XS Rating Curve= 0 ,0
Exp/Cntr(USF)=0,0
Exp/Cntr=0.3,0.1

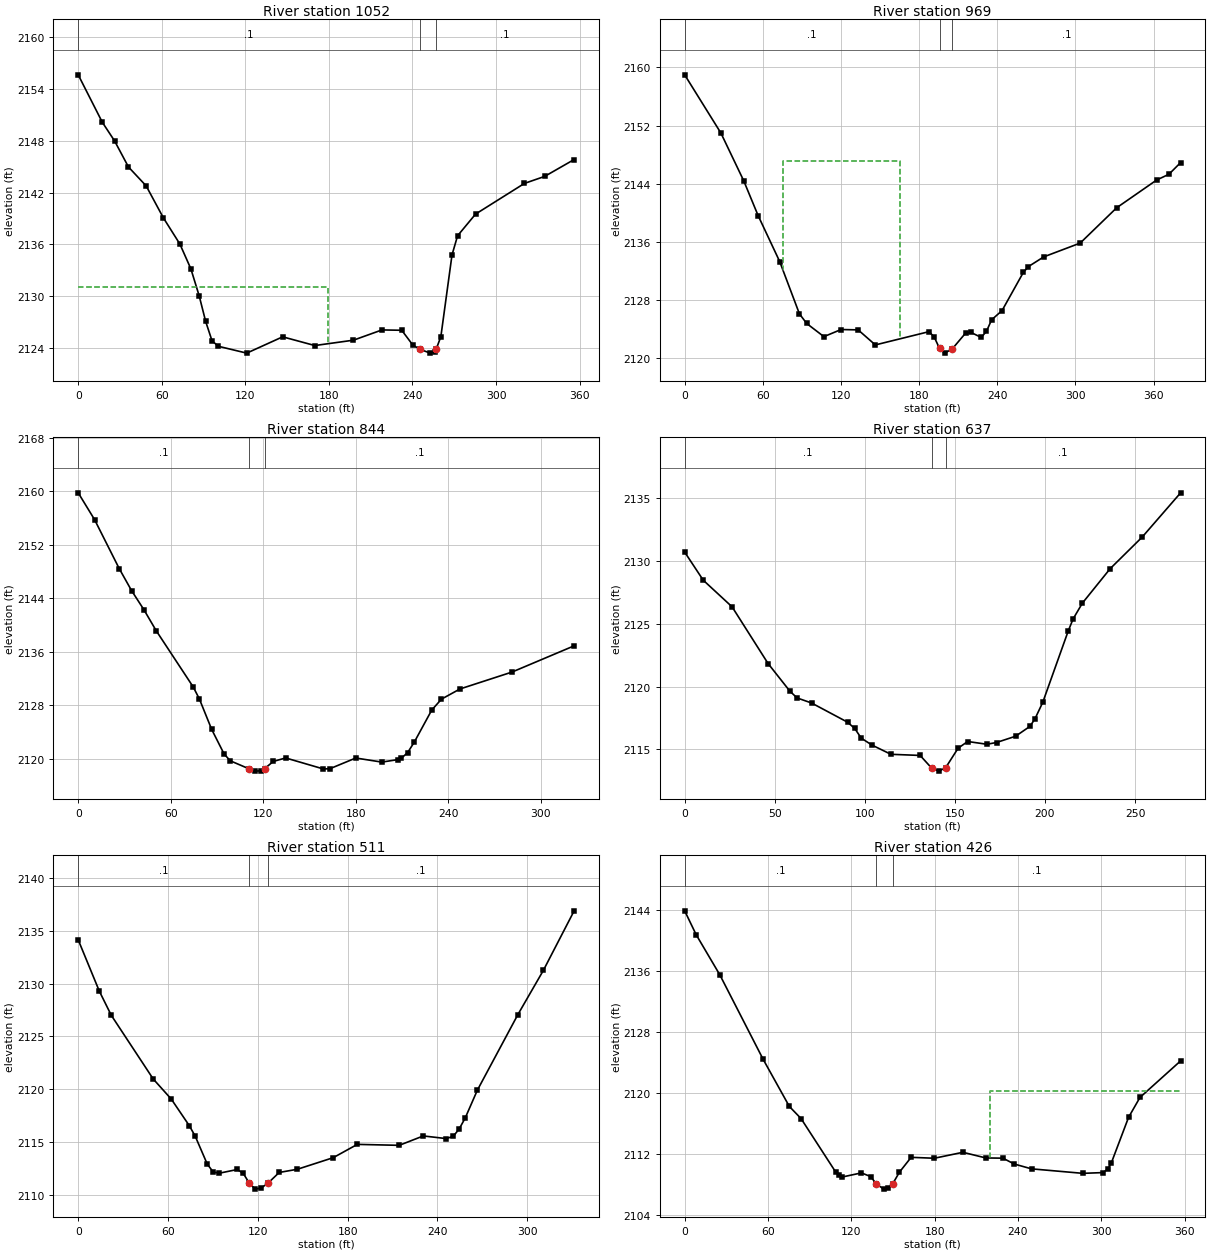
Type RM Length L Ch R = 1 ,1052    ,83.1,83.1,83.1
XS GIS Cut Line= 3
2218575.87285262664549.8728513352218684.55279411664738.958277993
2218677.48418003664876.796252567
#Sta/Elev= 30
       0 2155.65    17.3 2150.15    26.1 2147.99    36.1 2144.96    48.8 2142.77
    61.2 2139.05      73 2136.03    80.9 2133.15    86.9    2130    91.5 2127.06
    96.1  2124.8   100.7 2124.17     121 2123.38   146.8 2125.27   169.9 2124.26
   197.6 2124.88   218.1 2126.07   232.3 2126.03   240.3 2124.31   245.4 2123.83
   252.4  2123.4   256.4 2123.53   257.12123.863   260.4  2125.3   268.4 2134.77
   272.4 2136.99   285.3  2139.5   320.4 2143.06   334.9 2143.87   356.1 2145.83
#Mann= 3 ,-1,0
       0      .1       0   245.4    .045       0   257.1      .1       0
#XS Ineff= 2 , 0
          179.15 2131.01
Permanent Ineff=
       T       F
Bank Sta=245.4,257.1
XS Rating Curve= 0 ,0
Exp/Cntr(USF)=0,0
Exp/Cntr=0.3,0.1

Type RM Length L Ch R = 1 ,969     ,125.3,125.3,125.3
XS GIS Cut Line= 4
2218536.78543221664563.9217854262218603.19468585 664709.74829086
2218599.08689697664861.7364796222218602.51005437664930.199627713
#Sta/Elev= 30
       0 2158.98    27.8 2150.97    45.3 2144.41    56.4  2139.6      73 2133.26
    88.1 2126.08    93.7 2124.75   106.9 2122.94   120.1 2123.92   133.2 2123.87
   146.4  2121.8   187.7 2123.63   191.7 2122.85   195.7 2121.31   199.7 2120.67
   205.5 2121.26   215.7 2123.43   219.7 2123.53   227.7 2122.83   231.7 2123.67
   235.7 2125.26   243.7 2126.53     260 2131.77   263.9 2132.58   275.7 2133.92
   303.7 2135.82   331.7 2140.68   362.4  2144.5   371.8 2145.29   380.8  2146.9
#Mann= 3 ,-1,0
       0      .1       0   195.7    .045       0   205.5      .1       0
#XS Ineff= 1 ,-1
75.76516 165.297 2147.13
Permanent Ineff=
       T
Bank Sta=195.7,205.5
XS Rating Curve= 0 ,0
Exp/Cntr(USF)=0,0
Exp/Cntr=0.3,0.1

Type RM Length L Ch R = 1 ,844     ,206.7,206.7,206.7
XS GIS Cut Line= 3
2218482.86013778664606.6140522172218480.32446563664757.909157258
2218535.26402891664919.346950905
#Sta/Elev= 30
       0 2159.78    10.6 2155.78    26.6 2148.46    34.6 2145.17    42.6 2142.32
    50.6 2139.17    74.6 2130.77    78.6 2128.98    86.6 2124.42    94.6 2120.77
    98.6 2119.73   110.6 2118.55   114.6 2118.18   118.6 2118.23     1212118.565
   126.6 2119.63   134.6 2120.15     159 2118.51   163.2 2118.53   180.1 2120.14
     197 2119.53   207.4  2119.9   209.7 2120.12   213.7 2120.93   218.1 2122.53
   229.4 2127.31   235.7 2128.94   247.7 2130.46   281.5 2132.99   321.8 2136.91
#Mann= 3 ,-1,0
       0      .1       0   110.6    .045       0     121      .1       0
Bank Sta=110.6,121
XS Rating Curve= 0 ,0
Exp/Cntr(USF)=0,0
Exp/Cntr=0.3,0.1

Type RM Length L Ch R = 1 ,637     ,126.1,126.1,126.1
XS GIS Cut Line= 4
2218349.36517232664718.9021518492218354.35613582664816.725036368
2218430.21878095664903.0687048462218469.64739257664951.481050756
#Sta/Elev= 30
       0 2130.72    10.3 2128.48    26.3 2126.36    46.3 2121.84    58.4 2119.64
    62.4  2119.1    70.4  2118.7    90.4 2117.17    94.4 2116.67      98  2115.9
   103.9 2115.35   114.5 2114.61   130.7 2114.52   137.1 2113.51   141.2 2113.27
   144.9 2113.55   151.8  2115.1   157.1 2115.63   167.8 2115.41   173.1 2115.55
   183.7 2116.05   191.6 2116.83   194.4 2117.42   198.8 2118.76   212.9 2124.43
   215.6 2125.39   220.8 2126.66   236.2  2129.4     254 2131.92   275.3 2135.44
#Mann= 3 ,-1,0
       0      .1       0   137.1    .045       0   144.9      .1       0
Bank Sta=137.1,144.9
XS Rating Curve= 0 ,0
Exp/Cntr(USF)=0,0
Exp/Cntr=0.3,0.1

Type RM Length L Ch R = 1 ,511     ,84.7,84.7,84.7
XS GIS Cut Line= 2
2218292.20392072664727.1457995112218269.61108185665057.822804791
#Sta/Elev= 30
       0 2134.15    14.1 2129.29    22.1    2127    50.1 2120.97    62.2 2119.06
    74.2 2116.55    78.2 2115.54    86.2 2112.91    90.2 2112.15    94.3 2112.04
   106.3 2112.39   110.3 2112.02   114.3  2111.1   118.3 2110.53   122.3 2110.64
     127 2111.12   134.3 2112.11   146.4 2112.41   170.4 2113.51   186.5 2114.77
   214.5 2114.68   230.6 2115.57   245.9 2115.32   250.6 2115.53   254.6 2116.24
   258.6 2117.27   266.7  2119.9   293.8 2127.07   310.8 2131.25   331.4  2136.9
#Mann= 3 ,-1,0
       0      .1       0   114.3    .045       0     127      .1       0
Bank Sta=114.3,127
XS Rating Curve= 0 ,0
Exp/Cntr(USF)=0,0
Exp/Cntr=0.3,0.1

Type RM Length L Ch R = 1 ,426     ,95.2,95.2,95.2
XS GIS Cut Line= 3
2218242.20844708664700.8885228372218189.84834278664876.513039349
2218149.37981782665045.626202746
#Sta/Elev= 30
       0 2143.92     8.3 2140.78    25.3 2135.53    56.5 2124.45    75.4 2118.26
    83.8 2116.68   108.8 2109.65   111.2 2109.26     113 2108.99   127.3 2109.55
   133.9 2109.07     138 2108.12   143.3 2107.42   146.6 2107.52   149.8 2108.11
   154.7 2109.65   163.1 2111.59   179.8 2111.47   200.4 2112.25   216.9 2111.51
   229.2 2111.48   237.4 2110.71   249.8 2110.08   286.8 2109.49   301.4 2109.59
   304.7 2110.05   307.3 2110.86   319.7 2116.83   327.9 2119.44   357.2 2124.24
#Mann= 3 ,-1,0
       0      .1       0     138    .045       0   149.8      .1       0
#XS Ineff= 2 , 0
                          220.17         2120.33
Permanent Ineff=
       F       F
Bank Sta=138,149.8
XS Rating Curve= 0 ,0
Exp/Cntr(USF)=0,0
Exp/Cntr=0.3,0.1