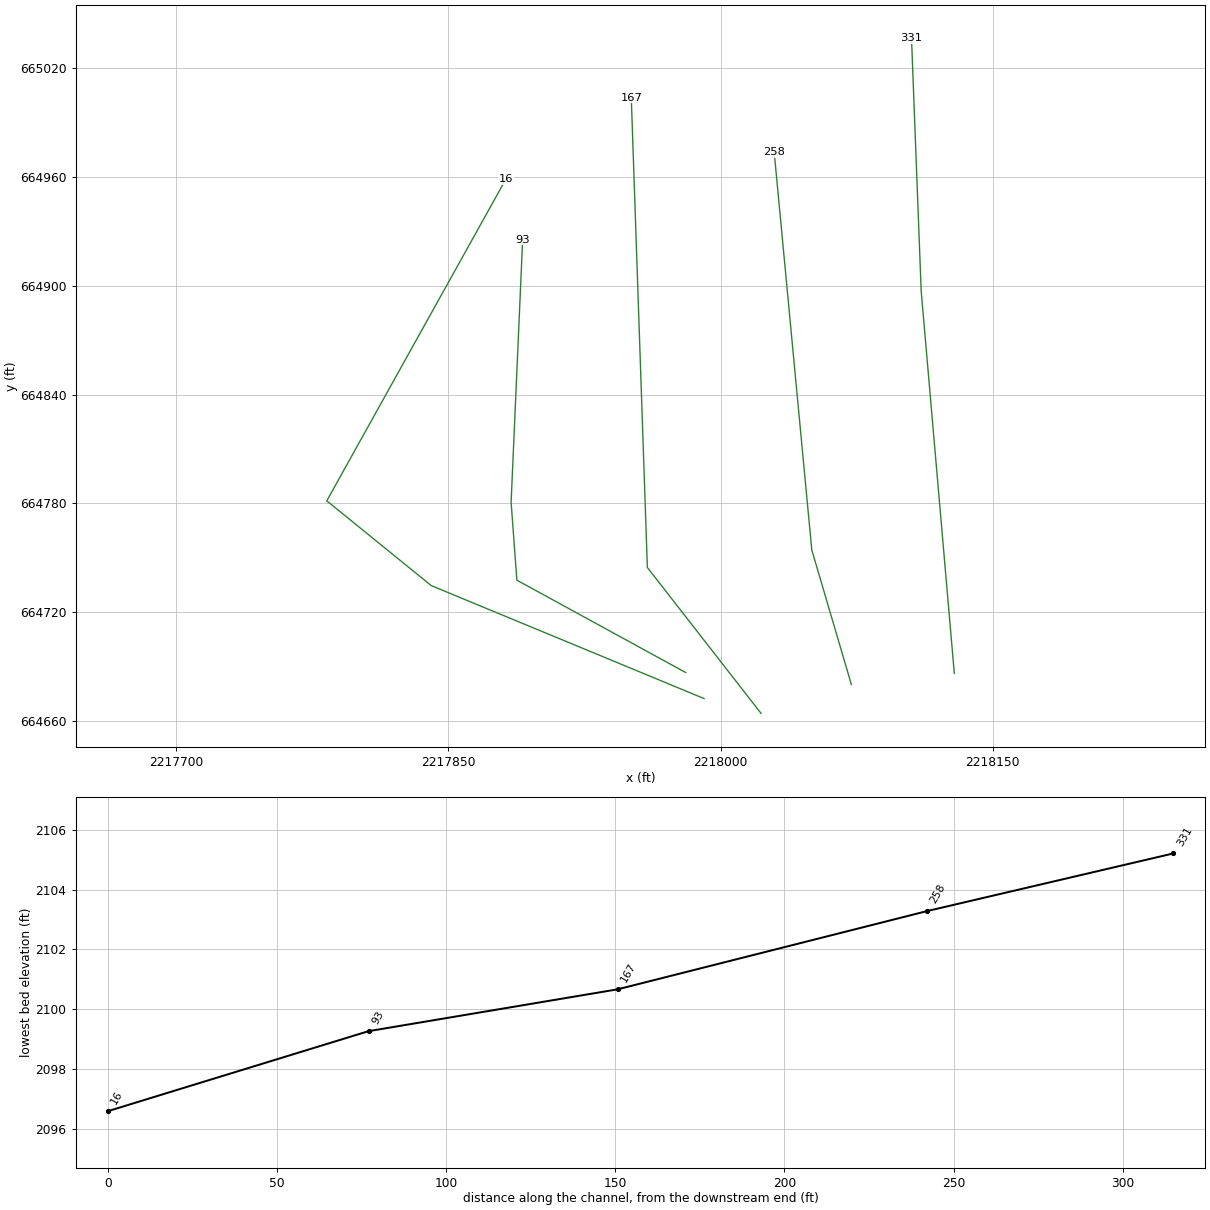
HEC-RAS study JENKSFKT1.prj: JENKSFKT1

--- JENKSFKT1.g01 (geometry) --- (continued)

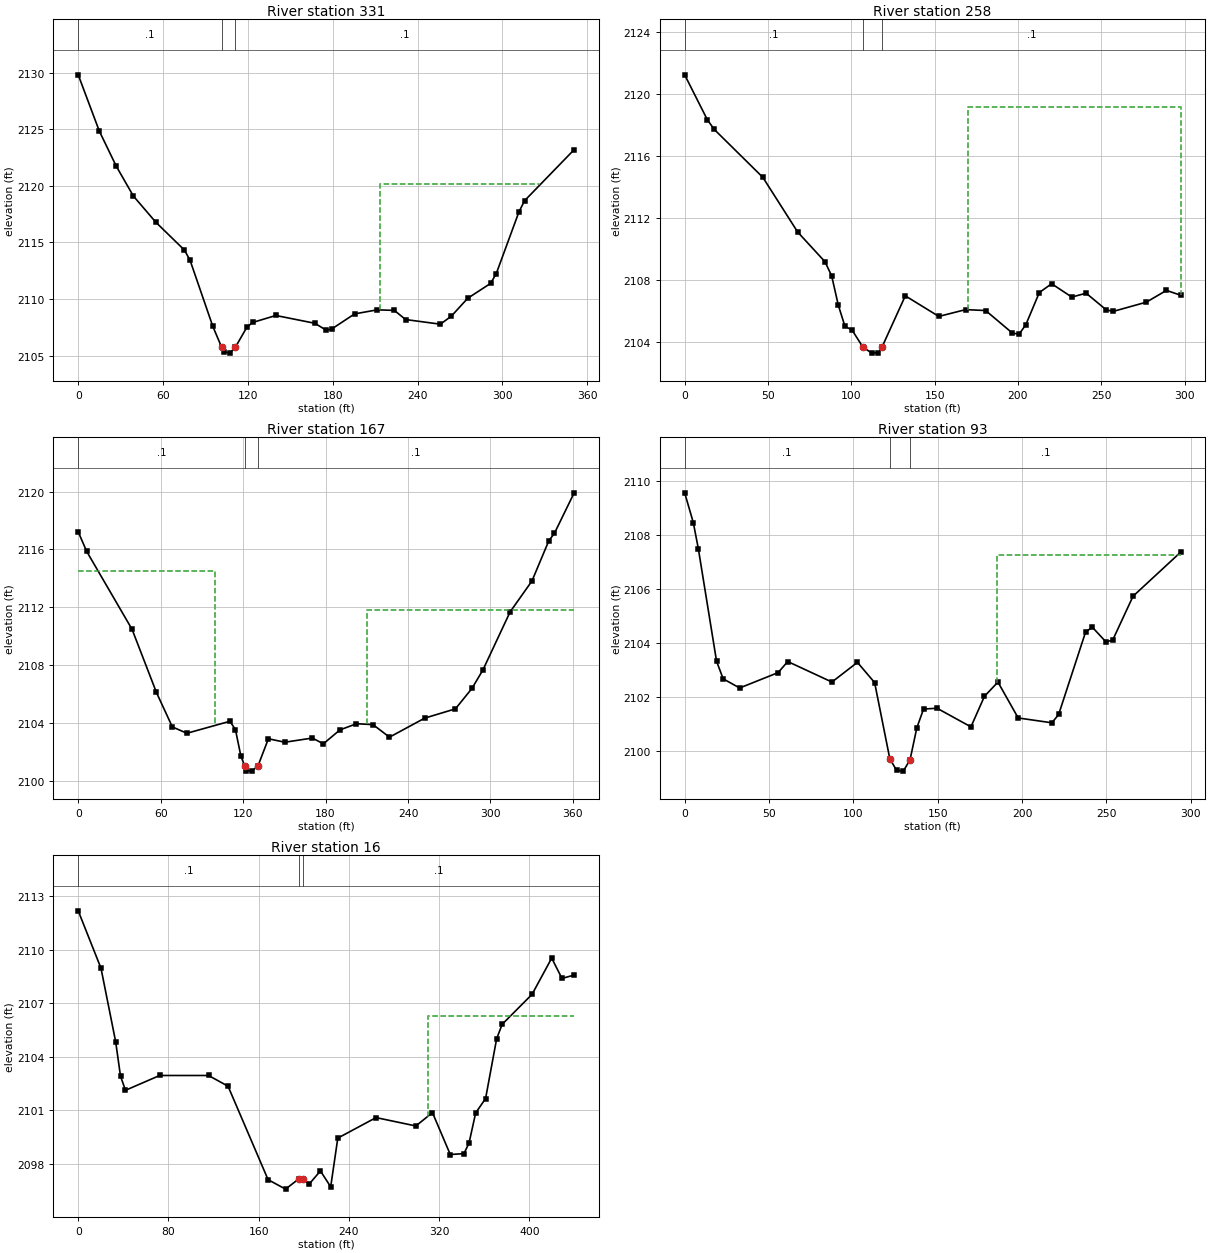
Type RM Length L Ch R = 1 ,331     ,72.8,72.8,72.8
XS GIS Cut Line= 3
2218128.75153471  664686.36933012218110.49469522664897.083685892
 2218105.1697837 665036.29208701
#Sta/Elev= 30
       0 2129.83    14.9 2124.86    26.9 2121.75      39 2119.11    54.9 2116.79
    75.1 2114.33    79.1 2113.43    95.2 2107.58   101.42105.747   103.2 2105.34
   107.2 2105.21   111.2 2105.74   119.3  2107.5   123.3 2107.92   139.8 2108.54
   167.4 2107.85   175.5 2107.23   179.5 2107.36   195.5 2108.68   211.5 2109.04
   223.6 2108.99   231.6 2108.18   256.2 2107.77     264 2108.49   275.5 2110.06
   291.7 2111.38   295.7 2112.24   311.7 2117.69   315.7 2118.69   350.8 2123.21
#Mann= 3 ,-1,0
       0      .1       0   101.4    .045       0   111.2      .1       0
#XS Ineff= 1 ,-1
213.3819326.1977 2120.18
Permanent Ineff=
       T
Bank Sta=101.4,111.2
XS Rating Curve= 0 ,0
Exp/Cntr(USF)=0,0
Exp/Cntr=0.3,0.1

Type RM Length L Ch R = 1 ,258     ,91.5,91.5,91.5
XS GIS Cut Line= 3
 2218072.0381081664680.1626482182218050.22139798664754.339462645
2218029.49552336664973.597399408
#Sta/Elev= 30
       0 2121.25    13.6 2118.35    17.7 2117.73    46.9 2114.63    67.8  2111.1
    84.2 2109.18    88.2 2108.27    92.2 2106.37    96.2    2105   100.3 2104.79
     1072103.663   112.3 2103.28   116.3 2103.31   118.5 2103.69   132.4 2106.98
   152.5 2105.65   168.6 2106.09   180.6 2106.03   196.7 2104.57   200.7 2104.51
   204.7 2105.11   212.8 2107.19   220.2 2107.76   232.3  2106.9   240.9 2107.15
   252.9 2106.08     257 2105.97     277 2106.57   289.1 2107.33   297.6 2107.02
#Mann= 3 ,-1,0
       0      .1       0     107    .045       0   118.5      .1       0
#XS Ineff= 2 , 0
                          169.98          2119.2
Permanent Ineff=
       F       F
Bank Sta=107,118.5
XS Rating Curve= 0 ,0
Exp/Cntr(USF)=0,0
Exp/Cntr=0.3,0.1

Type RM Length L Ch R = 1 ,167     ,73.6,73.6,73.6
XS GIS Cut Line= 3
2218022.25330435664664.3089823822217959.61005369664744.714086613
2217950.74734967665003.581916256
#Sta/Elev= 30
       0 2117.22     6.2 2115.86    39.2 2110.47    56.9 2106.11    68.5 2103.72
    79.1 2103.28   110.4 2104.11   114.4 2103.54   118.4 2101.69   121.2 2101.01
   122.4 2100.69   126.4 2100.66   130.92101.042   138.4  2102.9   150.4 2102.66
   170.4 2102.95   178.4 2102.55   190.4 2103.51   202.5 2103.94   214.5 2103.88
   226.5 2103.01   252.2 2104.33   274.5 2104.97   286.5 2106.38   294.5 2107.66
   314.3 2111.68   330.2 2113.82   342.5 2116.61   346.5 2117.11   360.9 2119.92
#Mann= 3 ,-1,0
       0      .1       0   121.2    .045       0   130.9      .1       0
#XS Ineff= 2 , 0
           99.83  2114.5  209.99         2111.83
Permanent Ineff=
       F       F
Bank Sta=121.2,130.9
XS Rating Curve= 0 ,0
Exp/Cntr(USF)=0,0
Exp/Cntr=0.3,0.1

Type RM Length L Ch R = 1 ,93      ,77.1,77.1,77.1
XS GIS Cut Line= 4
2217980.74826625664686.8112906292217887.70763342 664737.70531201
2217884.52675708 664780.647142552217890.88850975664925.377015853
#Sta/Elev= 30
       0 2109.57     5.1 2108.47     8.1  2107.5    18.9 2103.33    22.8 2102.68
    32.6 2102.34    55.4 2102.91    61.1 2103.32    87.3 2102.56   102.4 2103.29
   112.6 2102.54   121.6 2099.72   125.6 2099.29   129.6 2099.26   133.6 2099.68
   137.6 2100.86   141.6 2101.56   149.6 2101.59   169.7  2100.9   177.7 2102.03
   185.7 2102.56   197.7 2101.23   217.7 2101.05   221.7 2101.36   237.7 2104.42
   241.7 2104.59   249.7 2104.05   253.7 2104.11   265.8 2105.74     294 2107.37
#Mann= 3 ,-1,0
       0      .1       0   121.6    .045       0   133.6      .1       0
#XS Ineff= 2 , 0
                          185.03         2107.25
Permanent Ineff=
       F       F
Bank Sta=121.6,133.6
XS Rating Curve= 0 ,0
Exp/Cntr(USF)=0,0
Exp/Cntr=0.3,0.1

Type RM Length L Ch R = 1 ,16      ,,,
XS GIS Cut Line= 4
 2217990.8530307664672.4754349092217840.52763116664734.722832838
2217782.94573314664781.4223934292217881.54821383664958.536724531
#Sta/Elev= 30
       0 2112.18    20.2 2108.96    33.2 2104.84    37.5 2102.91    41.9 2102.12
    72.2 2102.95   115.5 2102.95   132.8 2102.35   168.3 2097.11   183.8 2096.58
   195.42097.149   199.2 2097.15   204.7 2096.86   214.7  2097.6   223.8 2096.71
   230.1 2099.44     264 2100.59   299.3 2100.12     314 2100.87   329.8 2098.52
   341.9 2098.57   346.4 2099.16   352.3 2100.85   361.1 2101.66   370.9 2105.01
   375.8 2105.82   402.3  2107.5   419.7 2109.53   428.8 2108.39   439.6 2108.58
#Mann= 3 ,-1,0
       0      .1       0   195.4    .045       0   199.2      .1       0
#XS Ineff= 2 , 0
                        309.6127         2106.27
Permanent Ineff=
       F       T
Bank Sta=195.4,199.2
XS Rating Curve= 0 ,0
Exp/Cntr(USF)=0,0
Exp/Cntr=0.3,0.1
LCMann Table=0

Chan Stop Cuts=-1
Use User Specified Reach Order=0
Composite Channel Slope=5